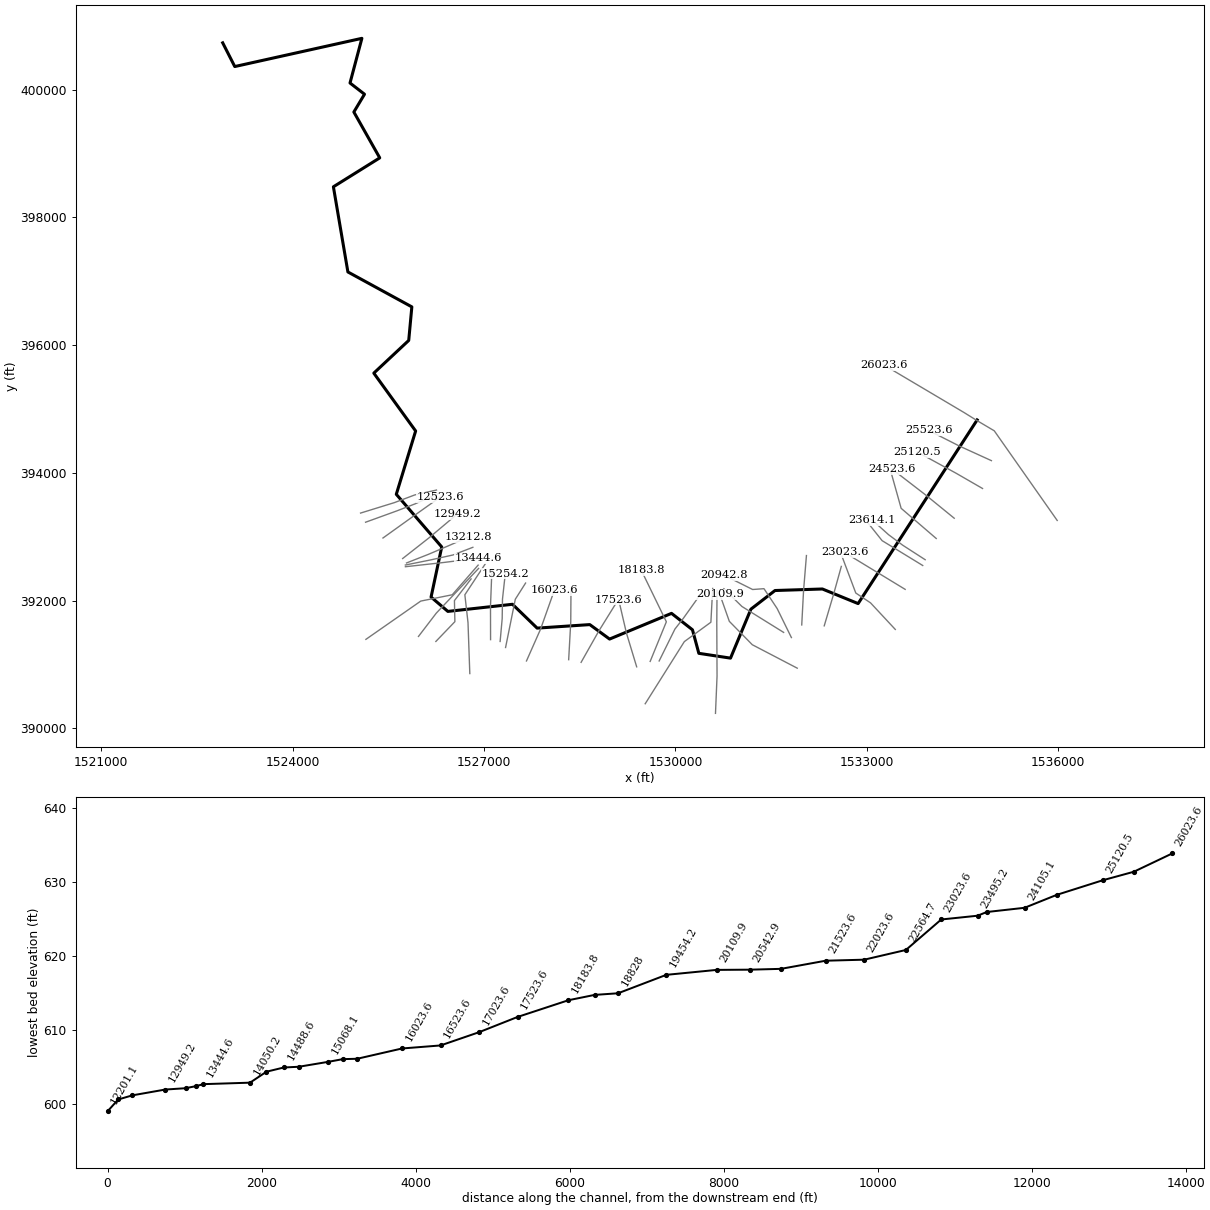
--- MILLCR.prj (project) ---

Proj Title=MILLCR
Current Plan=p01
Default Exp/Contr=0,0
English Units
Geom File=g01
Flow File=f01
Plan File=p01
BEGIN DESCRIPTION:
END DESCRIPTION:
DSS Export Rating Curves= 0
DSS Export Rating Curve Sorted= 0
DSS Export Volume Flow Curves= 0
DXF OffsetX= 0
DXF OffsetY= 0
DXF ScaleX= 0
DXF ScaleY= 0

--- MILLCR.p01 (plan) ---

Plan Title=Floodplain
Program Version=4.00
Geom File=g01
Flow File=f01
K Sum by GR=0
Std Step Tol=0.01
Critical Tol=0.01
Num of Std Step Trials=20
Max Error Tol=0.3
Flow Tol Ratio=0.001
Split Flow NTrial=30
Split Flow Tol=0.02
Split Flow Ratio=0.02
Log Output Level=0
Friction Slope Method=1
Unsteady Friction Slope Method=2
Unsteady Bridges Friction Slope Method=1
Global Log Level=0
CheckData=False
Run HTab=0
Run UNet=0
Run PostProcess=0
UNET Theta=0
UNET Theta Warmup=0
UNET ZTol=0
UNET ZSATol=0
UNET MxIter=0
UNET MaxInSteps=0
UNET DtIC=0
UNET DtMin=0
UNET MaxCRTS=0
UNET WFStab=0
UNET SFStab=0
UNET WFX=0
UNET SFX=0
UNET DSS MLevel=0
UNET DZMax Abort=0
UNET Convert EG Bridges=0
UNET Use Existing IB Tables=0
UNET Froude Limit=0
UNET Froude Power=0
Write IC File=0
Echo Input=False
Echo Output=False
Write Detailed=0

--- MILLCR.f01 (steady flow) ---

Flow Title=NFF Regression Equation
Program Version=4.00
Number of Profiles= 1
Profile Names=P100yr
River Rch & RM=MILLCR,Main            ,26023.6
    2504
River Rch & RM=MILLCR,Main            ,20942.8
    2659
River Rch & RM=MILLCR,Main            ,10788.8
    2934
River Rch & RM=MILLCR,Main            ,1028.8
    4800
Boundary for River Rch & Prof#=MILLCR,Main            , 1
Up Type= 0
Dn Type= 1
Dn Known WS=592.2
DSS Import GetInterval= 0
DSS Import GetPeak= 0
DSS Import FillOption= 0

--- MILLCR.g01 (geometry) ---

Geom Title=USGS 10m DEM
Program Version=4.00

River Reach=MILLCR          ,Main
Reach XY= 30
     1534728.436      394829.503     1532863.205      391954.754
     1532303.287      392183.322     1531560.709      392159.454
      1531183.36      391867.705     1530863.471      391101.073
     1530367.157      391176.193     1530267.261      391544.693
     1529938.976      391801.866      1528968.41      391399.572
     1528658.256      391625.875     1527832.797      391570.874
     1527446.985      391943.927     1526433.997      391832.424
     1526170.802      392056.879     1526337.726      392841.376
     1525625.836       393665.42     1525928.869      394656.516
     1525273.318      395562.178     1525820.587      396073.803
      1525869.36      396599.141     1524867.385      397145.535
     1524640.129      398478.787     1525366.457      398931.378
     1524960.703      399649.075     1525127.609      399927.628
     1524900.533      400103.328     1525086.601      400802.434
      1523094.41       400360.77     1522905.346      400732.064

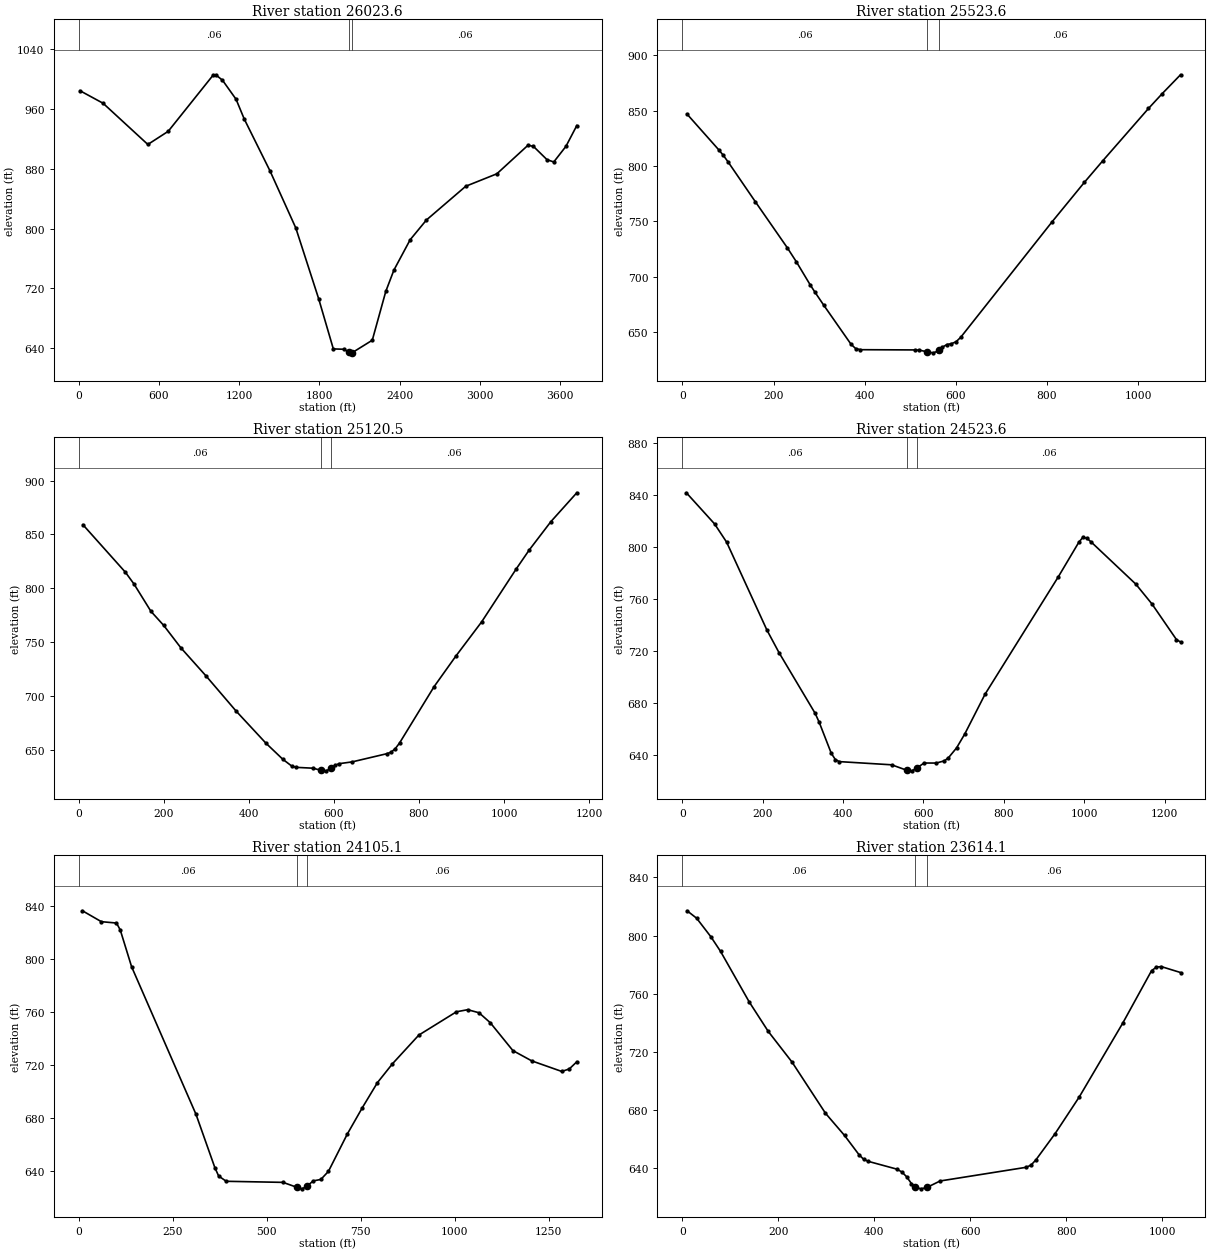
Type RM Length L Ch R = 1 ,26023.6 ,497.2,500,502.3
XS GIS Cut Line= 5
     1535983.166      393255.871     1534996.798      394659.237
     1534722.133      394821.791     1534524.886      394944.447
     1533269.493      395687.604
#Sta/Elev= 30
    10.1  984.44   182.7  967.69   517.6  912.56   669.9  930.14  1004.8 1005.06
  1025.1 1005.77  1075.9  998.48  1177.4     973  1238.3  946.67  1431.1  877.22
    1624   800.9  1795.1  706.18  1904.8  639.08  1984.6   638.6    2022  634.35
  2034.5  633.82    2047  634.15  2196.1  650.69  2297.2  716.07  2357.9  744.54
  2479.5  785.14  2601.1  811.53  2894.9  856.63  3127.9  873.33  3360.9  911.56
  3401.4  909.96  3502.8  892.22  3553.4  889.14  3644.6  910.09  3725.6  937.84
#Mann= 3 , 0 , 0
       0     .06       0    2022    .045       0    2047     .06       0
Bank Sta=2022,2047
XS Rating Curve= 0 ,0
Exp/Cntr=0.3,0.1

Type RM Length L Ch R = 1 ,25523.6 ,405.2,403.1,402.1
XS GIS Cut Line= 3
     1534952.044      394192.236     1534451.284      394420.218
     1533967.295      394665.572
#Sta/Elev= 30
      10  846.95      80  814.52      90  809.52     100  803.87   160.1  767.75
   230.1  726.26   250.1  713.52   280.1  692.95   290.1  686.59   310.1  674.39
   370.1  639.05   380.1  635.25   390.2  634.18   510.2  633.97   520.2  633.78
   537.7  632.17   550.2  631.34   560.3  632.81   562.7  633.68   570.3  636.41
   580.4  638.86   590.4  639.61   600.5  641.37   610.5   645.3   811.5  749.81
   881.8  785.15     922  804.55  1022.5  851.87  1052.6  865.25  1092.8   882.3
#Mann= 3 , 0 , 0
       0     .06       0   537.7    .045       0   562.7     .06       0
Bank Sta=537.7,562.7
XS Rating Curve= 0 ,0
Exp/Cntr=0.3,0.1

Type RM Length L Ch R = 1 ,25120.5 ,598,596.9,592.5
XS GIS Cut Line= 3
     1534813.115      393756.315     1534397.253      393995.964
     1533791.082      394327.244
#Sta/Elev= 30
      10  859.08     110  814.83     130  803.98     170  778.48     200  765.39
     240  744.71     300  718.17     370   685.8     440  655.98     480  640.89
   500.3   634.8   510.4  633.45   551.1  632.64   569.1  630.71   581.6  630.19
   594.1  632.64   601.9  635.19     612  636.84   642.5  638.49   723.8  646.07
   733.9  647.45   744.1  650.77   754.3  656.11   835.5  708.54   886.3  736.75
   947.3  768.78  1028.5  817.98    1059  835.55  1109.8  861.87  1170.8  888.75
#Mann= 3 , 0 , 0
       0     .06       0   569.1    .045       0   594.1     .06       0
Bank Sta=569.1,594.1
XS Rating Curve= 0 ,0
Exp/Cntr=0.3,0.1

Type RM Length L Ch R = 1 ,24523.6 ,424.7,418.5,415.7
XS GIS Cut Line= 3
     1534369.059      393291.114     1533926.137      393651.473
     1533396.366      394059.401
#Sta/Elev= 30
      10  841.69    80.1  817.83   110.2  803.78   210.4  736.33   240.4  719.05
   330.6  672.29   340.6  665.46   370.6  641.68   380.7   636.9   390.7   635.3
   520.9  632.85   558.5  628.66     571  628.22   583.5  630.38   601.4  634.22
   631.8   634.2     652  635.89   662.2  638.28   682.4  645.84   702.7  656.48
   753.4  687.14   935.7  777.26   986.4  803.61   996.5  807.45  1006.6  806.79
  1016.7  804.07  1128.2  771.62  1168.7  756.28  1229.5  728.99  1239.6  727.14
#Mann= 3 , 0 , 0
       0     .06       0   558.5    .045       0   583.5     .06       0
Bank Sta=558.5,583.5
XS Rating Curve= 0 ,0
Exp/Cntr=0.3,0.1

Type RM Length L Ch R = 1 ,24105.1 ,488.8,491,493.1
XS GIS Cut Line= 3
     1534087.119      392973.931     1533537.336      393446.181
      1533375.22      394024.158
#Sta/Elev= 30
    10.1  836.14    60.4  827.93   100.7  826.89   110.7  821.68   140.9  793.91
   312.1   682.7   362.4  642.39   372.4  636.15   392.6  632.16   543.6  631.35
   581.4  627.54   593.9  626.47   606.4   628.3   624.1  632.46   644.2  633.55
   664.4  639.64   714.7  667.84   754.8  687.77   794.8  706.58   834.8   720.8
   904.8   742.4  1004.9  759.98  1034.9  761.55  1064.9  759.24  1094.9  751.73
    1155  730.72    1205  722.98    1285  714.99    1305  716.87    1325  722.26
#Mann= 3 , 0 , 0
       0     .06       0   581.4    .045       0   606.4     .06       0
Bank Sta=581.4,606.4
XS Rating Curve= 0 ,0
Exp/Cntr=0.3,0.1

Type RM Length L Ch R = 1 ,23614.1 ,116.1,118.9,121.7
XS GIS Cut Line= 4
     1533913.966      392641.709     1533562.898      392868.055
     1533338.862       393034.35       1533084.8      393263.006
#Sta/Elev= 30
     9.9   817.1    29.8  811.98    59.7  799.13    79.6   789.2   139.2  754.54
     179  734.19   228.7  713.04   298.4  677.87   338.1  662.61     368  649.49
   377.9  646.21   387.9  644.77   447.6  639.41   457.6  637.47   467.5  634.24
   477.5  629.55   484.9  627.22   497.4   625.9   509.9  626.86   537.3   631.3
   716.8  640.71   726.9  642.23   736.9  645.76   777.1  663.88   827.4  689.06
   917.9  739.74   978.2  775.93   988.3  778.36   998.3  778.73  1038.5  774.65
#Mann= 3 , 0 , 0
       0     .06       0   484.9    .045       0   509.9     .06       0
Bank Sta=484.9,509.9
XS Rating Curve= 0 ,0
Exp/Cntr=0.3,0.1

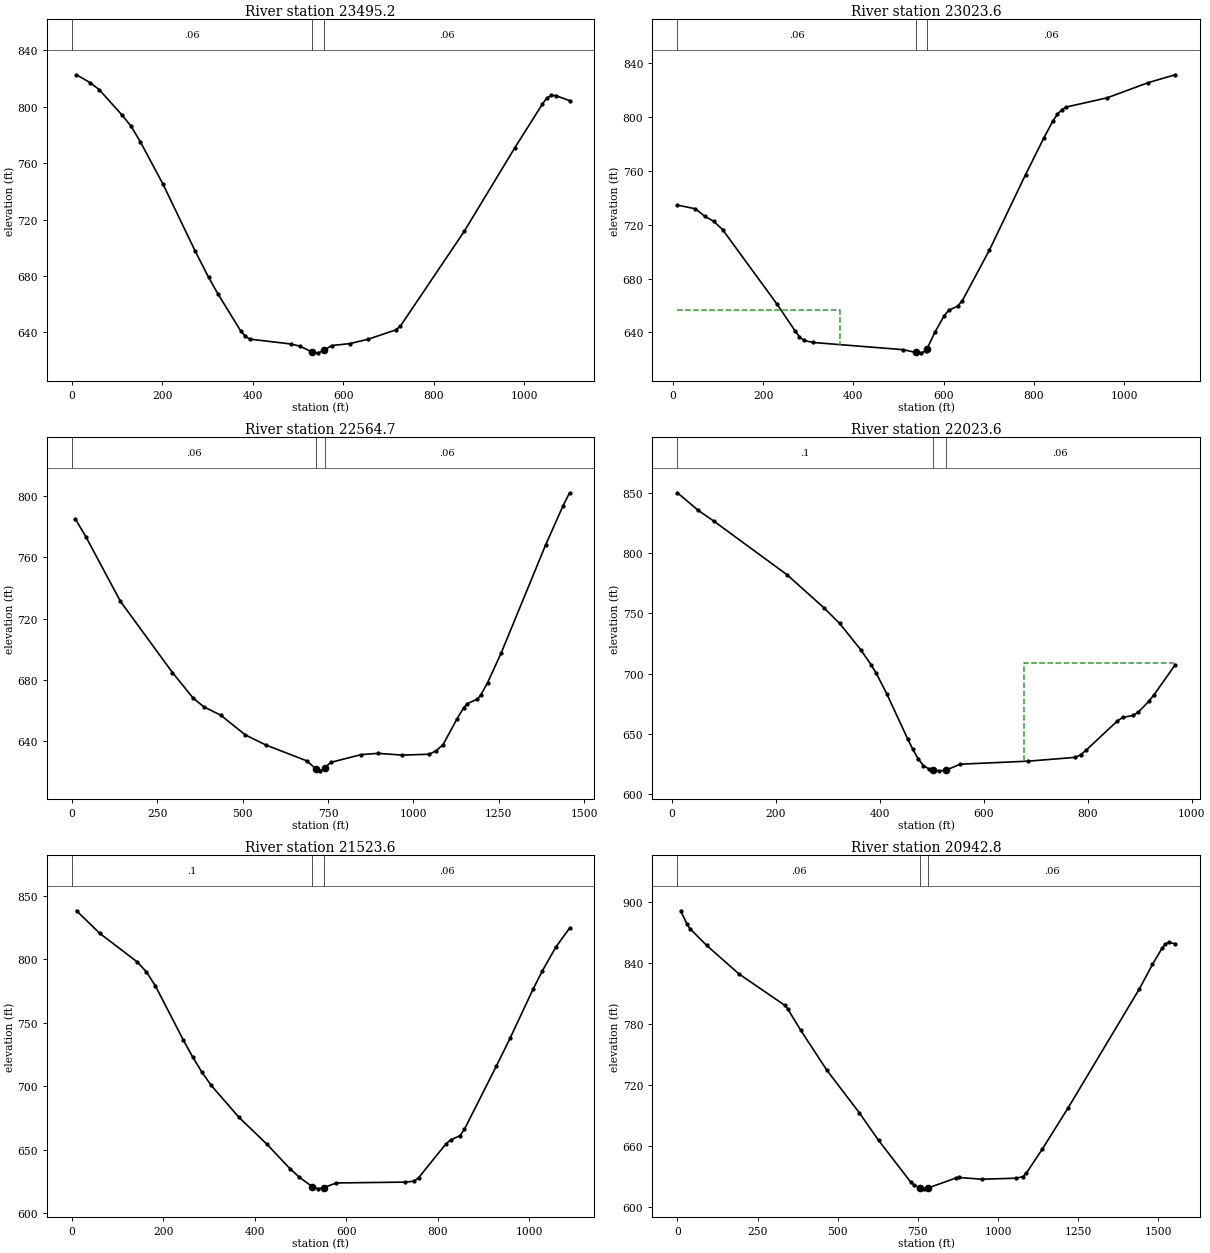
Type RM Length L Ch R = 1 ,23495.2 ,471.8,471.6,471.3
XS GIS Cut Line= 3
     1533875.664      392551.022     1533239.547      392939.654
     1533018.602      393216.715
#Sta/Elev= 30
    10.1  822.76    40.3   817.2    60.4  812.22   110.8   794.2     131  786.17
   151.1  775.31   201.5  745.06     272  697.95   302.2  678.94   322.4  667.43
   372.7  641.15   382.8  637.37   392.9  635.14   483.5   631.7   503.7   630.2
   531.5  625.84     544   625.4   556.5  627.12   574.2  630.59   614.5  631.97
   654.8  635.09   715.2  641.61   725.3   644.1   866.9  711.61   978.3  770.71
  1039.1  801.68  1049.2  806.22  1059.3  808.09  1069.4  807.97  1099.8  804.42
#Mann= 3 , 0 , 0
       0     .06       0   531.5    .045       0   556.5     .06       0
Bank Sta=531.5,556.5
XS Rating Curve= 0 ,0
Exp/Cntr=0.3,0.1

Type RM Length L Ch R = 1 ,23023.6 ,460.1,459,457.8
XS GIS Cut Line= 3
     1533600.255      392177.565     1533129.751      392463.549
     1532649.225      392755.428
#Sta/Elev= 30
      10  734.52    50.1  731.74    70.1  726.28    90.1  722.56   110.1  716.35
   230.3  661.21   270.3  641.42   280.3  636.97   290.3  634.09   310.3  632.59
   510.6  627.23   538.1  625.15   550.6  624.89   560.6  626.32   563.1   627.9
   580.7  640.27   600.8   652.2   610.8  656.38   630.9  659.53     641   663.4
   701.2  701.02   781.5  757.14   821.7  784.15   841.8  796.81   851.8  801.76
   861.8  805.31   871.9  807.27   962.2  814.07  1052.6  825.27  1112.8  831.17
#Mann= 3 , 0 , 0
      10     .06       0   538.1    .045       0   563.1     .06       0
#XS Ineff= 2 , 0
          369.85  656.45
Permanent Ineff=
       F       F
Bank Sta=538.1,563.1
XS Rating Curve= 0 ,0
Exp/Cntr=0.3,0.1

Type RM Length L Ch R = 1 ,22564.7 ,576.3,541,506.2
XS GIS Cut Line= 4
     1533445.705      391550.134     1533058.038      391965.996
     1532826.478      392120.385     1532611.514      392691.685
#Sta/Elev= 30
    10.2  784.88    40.6  773.42   142.1  731.22   294.4  684.83   355.3  668.12
   385.8  662.56   436.6  656.92   507.6  644.22   568.5  637.56   687.8  627.27
   715.1  621.87   727.6  620.77   740.1  622.56   757.4  626.24   846.8  631.34
   896.9  632.16   966.9  631.01    1047  631.59    1067  633.94    1087  637.91
    1127  654.41    1147  661.78    1157  664.48  1187.1  667.48  1197.1  670.13
  1217.1  678.22  1257.1  697.63  1387.2  768.02  1437.2  793.05  1457.2  801.91
#Mann= 3 , 0 , 0
       0     .06       0   715.1    .045       0   740.1     .06       0
Bank Sta=715.1,740.1
XS Rating Curve= 0 ,0
Exp/Cntr=0.3,0.1

Type RM Length L Ch R = 1 ,22023.6 ,493.7,500,505
XS GIS Cut Line= 3
     1532332.042      391606.522     1532481.064      392108.876
     1532599.885      392536.924
#Sta/Elev= 30
    10.1   849.8    50.4  835.19    80.6  826.22   221.7  781.71   292.2  754.51
   322.5  741.54   362.8  719.89   382.9  707.43     393  700.16   413.1  683.37
   453.5  645.83   463.5  637.15   473.6  629.35   483.7  623.83   493.8  621.17
   501.4  620.31   513.9  619.46   526.4  619.85   554.3  624.96   685.5  627.48
   776.4  630.64   786.5  632.81   796.6  636.44   857.2  660.87   867.3   663.7
   887.5  665.39   897.6  668.24   917.7  677.11   927.8  682.56   968.2  707.23
#Mann= 3 , 0 , 0
    10.1      .1       0   501.4    .045       0   526.4     .06       0
#XS Ineff= 2 , 0
                           676.4          708.97
Permanent Ineff=
       F       F
Bank Sta=501.4,526.4
XS Rating Curve= 0 ,0
Exp/Cntr=0.3,0.1

Type RM Length L Ch R = 1 ,21523.6 ,563,580.9,599.6
XS GIS Cut Line= 3
     1531979.617      391620.619     1532008.228      392158.482
     1532053.295      392706.869
#Sta/Elev= 30
    10.2  838.32      61  820.54   142.3  798.25   162.6  790.44   182.9  779.07
   243.9  736.52   264.2   723.2   284.6  711.16   304.9  700.76   365.9  675.52
   426.8  654.43   477.6  635.03     498  628.39   526.1  620.98   538.6  619.32
   551.1  620.27   578.6  623.96   728.7  624.61   748.7  625.34   758.7  628.15
   818.7  654.87   828.7  657.83   848.8  661.12   858.8  666.22   928.8  716.07
   958.8  738.04  1008.8  776.43  1028.8  790.65  1058.8  809.72  1088.9  824.66
#Mann= 3 , 0 , 0
       0      .1       0   526.1    .045       0   551.1     .06       0
Bank Sta=526.1,551.1
XS Rating Curve= 0 ,0
Exp/Cntr=0.3,0.1

Type RM Length L Ch R = 1 ,20942.8 ,388.4,399.9,411.6
XS GIS Cut Line= 5
     1531817.502      391423.261     1531594.028       391877.55
      1531387.75      392188.274     1531210.193      392175.218
     1530767.275      392395.954
#Sta/Elev= 30
    10.1  891.47    30.4  878.08    40.5  873.45    91.1   857.5   192.4  829.32
   334.1  798.76   344.3  794.91   384.8  773.96   465.8  734.95   566.8   693.2
   627.2  665.96     728  624.71   738.1  621.87   755.9     619   768.4  618.22
   780.9  618.96   869.2  628.91   879.2  629.38   948.5  627.67  1057.3  628.68
  1077.5  630.26  1087.6  633.39  1138.1  657.28  1218.9  697.98  1441.1  814.91
  1481.5  838.68  1511.8  854.88  1521.9     859    1532  860.51  1552.2  859.04
#Mann= 3 , 0 , 0
       0     .06       0   755.9    .045       0   780.9     .06       0
Bank Sta=755.9,780.9
XS Rating Curve= 0 ,0
Exp/Cntr=0.3,0.1

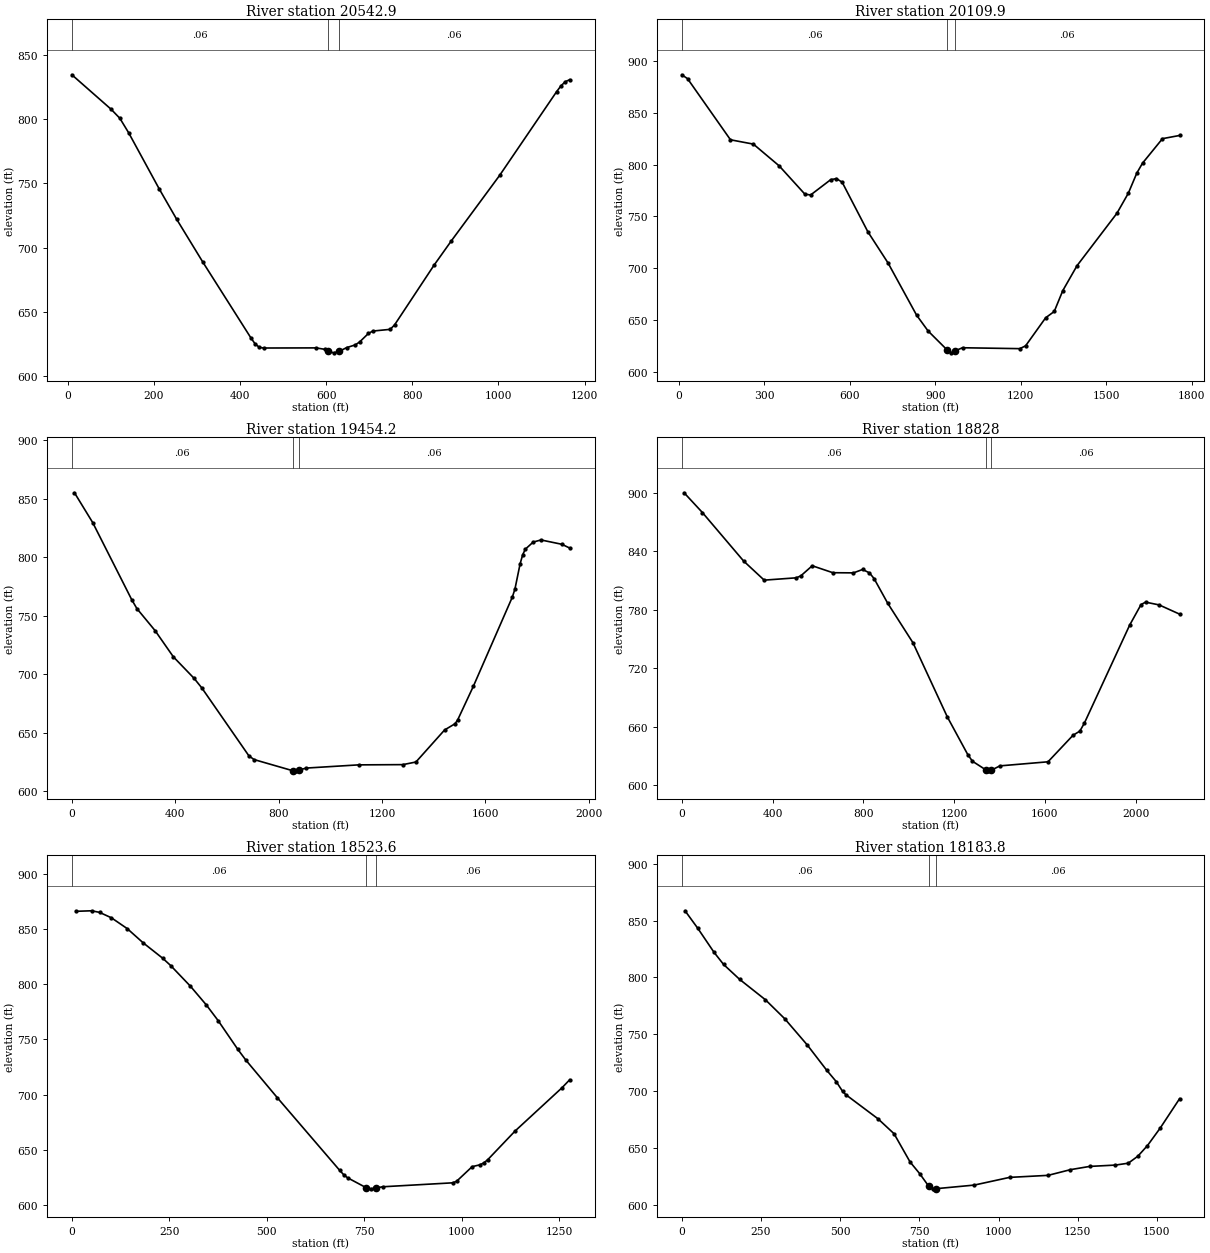
Type RM Length L Ch R = 1 ,20542.9 ,439.4,433,426.3
XS GIS Cut Line= 3
     1531695.573       391504.05     1531042.167      391909.608
     1530759.934      392187.541
#Sta/Elev= 30
    10.1  834.42   101.2  807.58   121.4  800.59   141.7   789.4   212.5  745.81
     253  722.18   313.7  688.85     425  630.01   435.1  625.15   445.2  622.33
   455.4  621.86   576.8  621.96     597  620.84   604.8  619.49  617.21  618.11
   629.8  619.16   647.6  622.17   667.8   624.3     678  626.63   698.2   633.2
   708.3  635.05   748.8  636.39   758.9  639.85   850.3  686.21   890.9  705.35
  1002.6  756.12  1134.7   821.2  1144.8  825.73    1155  829.06  1165.1  830.57
#Mann= 3 , 0 , 0
    10.1     .06       0   604.8    .045       0   629.8     .06       0
Bank Sta=604.8,629.8
XS Rating Curve= 0 ,0
Exp/Cntr=0.3,0.1

Type RM Length L Ch R = 1 ,20109.9 ,677.1,655.7,634.4
XS GIS Cut Line= 4
     1531909.132      390943.963     1531204.698      391310.894
     1530844.809      391677.007     1530694.917      392101.411
#Sta/Elev= 30
    10.1   886.9    30.2  883.17     181  824.05   261.4  819.87   351.9  798.86
   442.4  771.44   462.5  770.72   532.9   785.5     553  786.52   573.1  783.02
   663.6  734.99   733.9  705.09   834.5  654.47   874.8  639.21   942.8  620.57
  955.54  618.08   967.8  619.81   995.6     623  1196.9  622.13  1217.1  624.85
  1287.5  651.97  1317.7  658.07  1347.7  678.23  1397.7  702.34  1537.7  752.98
  1577.7  772.35  1607.7  791.92  1627.7  801.48  1697.7  825.14  1757.7  828.23
#Mann= 3 , 0 , 0
    10.1     .06       0   942.8    .045       0   967.8     .06       0
Bank Sta=942.8,967.8
XS Rating Curve= 0 ,0
Exp/Cntr=0.3,0.1

Type RM Length L Ch R = 1 ,19454.2 ,653.4,626.2,598.9
XS GIS Cut Line= 4
     1530627.913      390236.379     1530652.393      390819.802
     1530648.313      391648.017     1530652.393      392162.081
#Sta/Elev= 30
    10.1  855.14    80.5  829.71   231.6  763.75   251.7  756.11   322.2  737.25
   392.6  714.92   473.2  696.44   503.4  688.14   684.9  630.28   705.1  627.04
   854.2  617.55   866.7  617.41   879.2  618.11   907.1  619.78  1109.2  622.51
  1280.9  622.72  1331.4  624.96  1442.4  652.37  1482.7  657.66  1492.8  660.89
  1553.3  689.55  1704.5  765.99  1714.6  772.88  1734.7  794.56  1744.8  802.29
  1754.9  806.95  1785.1  812.98  1815.4  814.81    1896  811.11  1926.2  807.91
#Mann= 3 , 0 , 0
       0     .06       0   854.2    .045       0   879.2     .06       0
Bank Sta=854.2,879.2
XS Rating Curve= 0 ,0
Exp/Cntr=0.3,0.1

Type RM Length L Ch R = 1 ,18828   ,296.8,304.4,313.3
XS GIS Cut Line= 4
     1529526.739      390387.132     1530139.959      391359.825
      1530555.82       391662.91     1530584.014      392191.548
#Sta/Elev= 30
    10.1  899.97    90.8  879.72   272.3  830.04   363.1  810.41   504.3  812.79
   524.5   814.8   574.9  825.15   665.7  818.03   756.5  817.86   796.8  821.33
   827.1  817.86   847.3  812.04   907.8   786.6  1018.7  746.25    1170   670.3
  1260.8  631.39    1281  624.76  1339.2  616.02  1351.7  614.92  1364.2  615.59
  1402.1  620.01    1614  624.19  1724.4  651.42  1754.3  655.64  1774.3  663.84
  1974.1  764.42    2024  785.38    2044  787.85  2103.9  785.01  2193.8  775.57
#Mann= 3 , 0 , 0
       0     .06       0  1339.2    .045       0  1364.2     .06       0
Bank Sta=1339.2,1364.2
XS Rating Curve= 0 ,0
Exp/Cntr=0.3,0.1

Type RM Length L Ch R = 1 ,18523.6 ,309,339.8,369.4
XS GIS Cut Line= 4
     1529745.243      391056.739     1529992.636      391556.636
     1530122.005       391721.21     1530418.627      392136.181
#Sta/Elev= 30
    10.1  866.12    50.7  866.61      71  865.17   101.4  860.26     142  850.47
   182.5   837.7   233.2  823.56   253.5     817   304.2  798.27   344.8   781.4
   375.2  767.17   425.9  741.01   446.2  731.43   527.3   697.2   687.4  631.35
   697.3  627.56   707.3  624.74   754.6  615.85   767.1   614.7   779.6  615.39
   797.1  616.56   977.1  620.15   987.1  621.53  1027.1   634.8  1047.1  636.47
  1057.1  638.23  1067.1  641.12  1137.2  667.07  1257.2  706.14  1277.2  713.47
#Mann= 3 , 0 , 0
       0     .06       0   754.6    .045       0   779.6     .06       0
Bank Sta=754.6,779.6
XS Rating Curve= 0 ,0
Exp/Cntr=0.3,0.1

Type RM Length L Ch R = 1 ,18183.8 ,664.7,660.2,653.9
XS GIS Cut Line= 3
     1529604.273      391049.691     1529858.019      391669.959
     1529463.303      392480.536
#Sta/Elev= 30
    10.2  858.59    50.8  843.05   101.5  822.15     132  811.35   182.8  798.21
     264  780.31   324.9  763.65     396   740.6   456.9  718.54   487.4   708.4
   507.7  699.75   517.9  696.81   619.4  675.62   670.2  662.46   720.8   637.6
   751.2  627.32   779.2  616.44   791.7  613.98   804.2  614.15   923.4  617.28
  1034.8  624.05  1156.4  625.84  1227.3  630.86  1288.1  633.71  1369.1  634.88
  1409.7  636.54    1440  642.69  1470.4  652.06    1511  667.61  1571.7  693.26
#Mann= 3 , 0 , 0
       0     .06       0   779.2    .045       0   804.2     .06       0
Bank Sta=779.2,804.2
XS Rating Curve= 0 ,0
Exp/Cntr=0.3,0.1

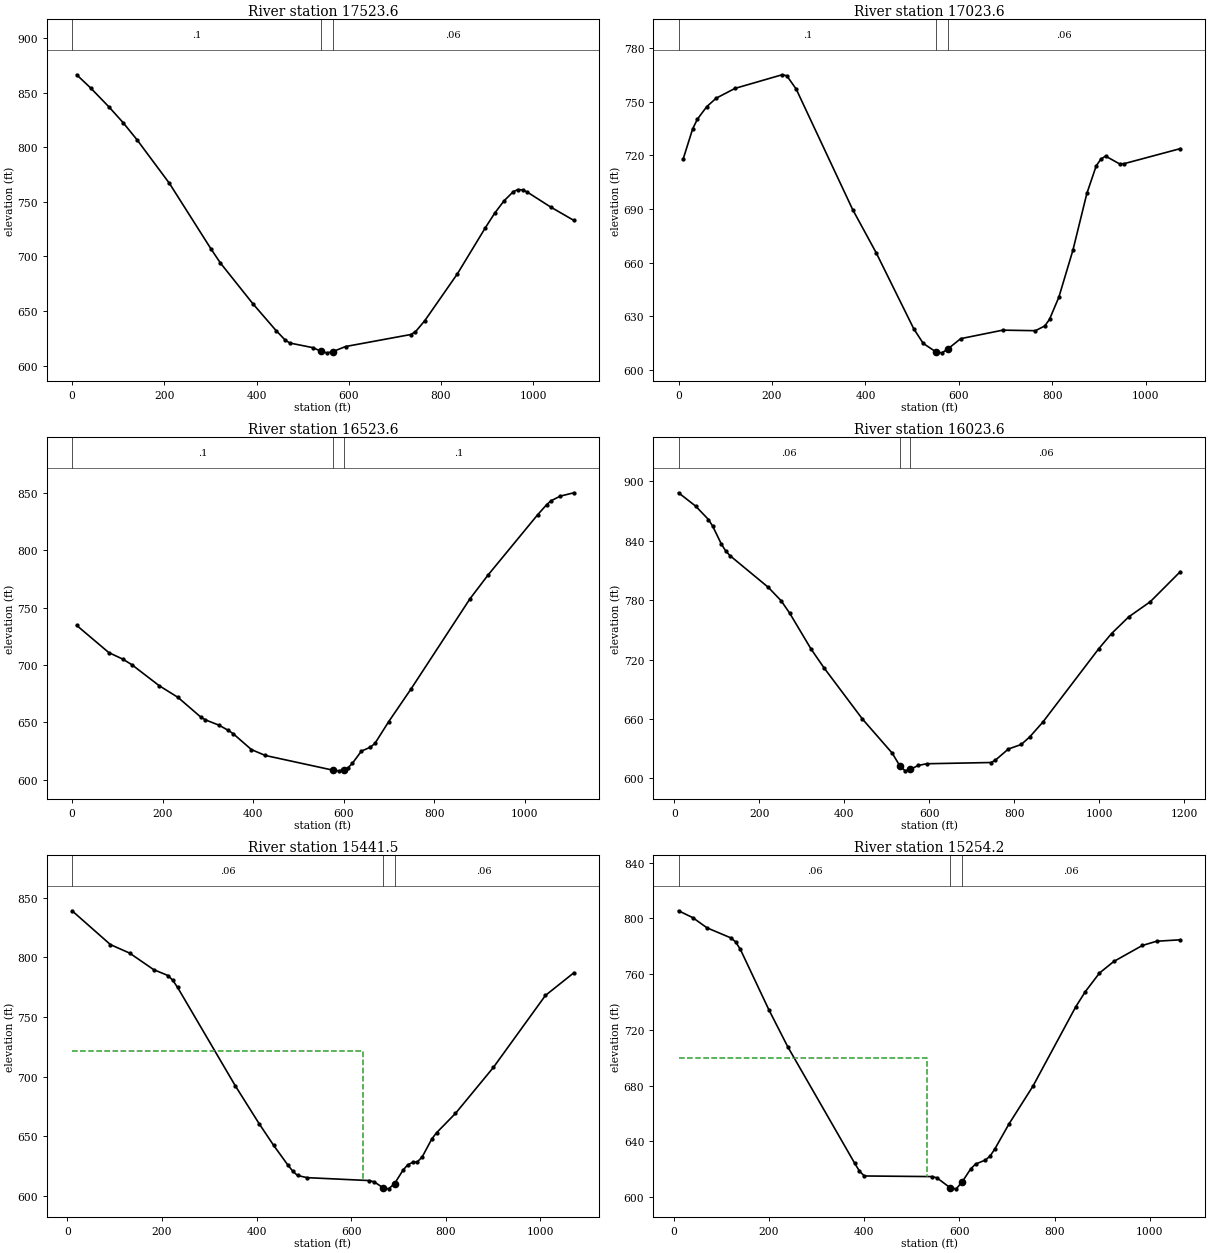
Type RM Length L Ch R = 1 ,17523.6 ,522.1,500,478.5
XS GIS Cut Line= 3
     1529392.818      390965.109     1529232.252      391494.006
     1529110.878      392015.335
#Sta/Elev= 30
      10   866.4    40.2  854.35    80.4  836.78   110.5  822.65   140.7  806.94
     211     767   301.5  706.71   321.6  694.03   391.9  656.77   442.2  632.18
   462.3  623.33   472.3   620.7   522.6  616.42   540.2  613.04   552.7  611.72
   565.2  612.82   593.1  617.51   734.5  628.51   744.6  631.04   764.8  641.19
   835.5  684.12   896.1   726.3   916.3   739.6   936.5   750.9   956.7  759.36
   966.8  761.28   976.9  760.95     987  758.96  1037.5  745.32    1088  733.01
#Mann= 3 , 0 , 0
       0      .1       0   540.2    .045       0   565.2     .06       0
Bank Sta=540.2,565.2
XS Rating Curve= 0 ,0
Exp/Cntr=0.3,0.1

Type RM Length L Ch R = 1 ,17023.6 ,488.1,500,514.5
XS GIS Cut Line= 3
     1528521.982      391035.167     1528799.669      391525.748
     1529068.587      391958.947
#Sta/Elev= 30
    10.1  718.13    30.2  734.81    40.3  740.24    60.4  747.25    80.5  751.97
   120.8  757.45   221.5  765.06   231.5  764.56   251.7  757.09   372.5  689.76
   422.8  665.62   503.3  623.09   523.5  614.94   551.2   610.1   563.7  609.66
   576.2  611.83   603.7  617.59   693.7  622.34   763.7  622.04   783.7  624.71
   793.7  628.38   813.7  640.77   843.7  666.94   873.6  698.72   893.6  714.14
   903.6  717.91   913.6  719.63   943.6  715.25   953.6   715.4  1073.6  723.79
#Mann= 3 , 0 , 0
       0      .1       0   551.2    .045       0   576.2     .06       0
Bank Sta=551.2,576.2
XS Rating Curve= 0 ,0
Exp/Cntr=0.3,0.1

Type RM Length L Ch R = 1 ,16523.6 ,509.7,500,491
XS GIS Cut Line= 3
     1528327.103      391076.709     1528359.703      391665.183
     1528363.737      392184.499
#Sta/Elev= 30
    10.2   734.5    81.3   710.8   111.8  705.19   132.1  700.29   193.1  681.84
   233.7  671.93   284.5  654.65   294.7  652.24   325.2  647.54   345.5  643.01
   355.7   640.3   396.3  626.37   426.8  621.27   576.9  608.41   589.4  607.87
   601.9  608.95   609.4  610.41   619.3   614.4   639.3  625.04   659.3  628.51
   669.3  631.81   699.2  650.49   749.2  679.33     879  757.59     919  778.33
  1028.8   830.9  1048.8  839.72  1058.8  843.13  1078.7  847.08  1108.7  849.99
#Mann= 3 , 0 , 0
       0      .1       0   576.9    .045       0   601.9      .1       0
Bank Sta=576.9,601.9
XS Rating Curve= 0 ,0
Exp/Cntr=0.3,0.1

Type RM Length L Ch R = 1 ,16023.6 ,575.6,582.1,586.5
XS GIS Cut Line= 3
     1527665.935      391056.739     1527886.056      391553.437
     1528102.942      392163.354
#Sta/Elev= 30
    10.1  888.59    50.3  875.12    80.5  861.55    90.5  854.82   110.7  836.84
   120.7  830.02   130.8  825.14   221.3     793   251.5  779.42   271.6  766.85
   321.9   730.6   352.1  711.74   442.7  659.86   513.1  625.19   530.8  612.41
  543.22  607.46   555.8  608.97   573.6  612.87   593.9  614.63   745.6  615.88
   755.7  618.31     786   629.5   816.4  634.11   836.6  641.89     867  656.64
   998.4  730.76  1028.8  746.25  1069.2  763.12  1119.8   778.4  1190.6  808.88
#Mann= 3 , 0 , 0
    10.1     .06       0   530.8    .045       0   555.8     .06       0
Bank Sta=530.8,555.8
XS Rating Curve= 0 ,0
Exp/Cntr=0.3,0.1

Type RM Length L Ch R = 1 ,15441.5 ,182.3,187.3,192.4
XS GIS Cut Line= 3
     1527338.384      391267.466     1527490.821      392022.722
     1527651.838       392276.13
#Sta/Elev= 30
    10.1  839.16    91.2   810.8   131.8  803.67   182.5  789.83   212.9  784.87
     223  780.87   233.2  774.86   354.8  692.65   405.5  660.68   435.9  642.66
   466.3  625.98   476.5   620.9   486.6  617.26   506.9  615.45   638.7  612.99
   648.8  611.88   666.7  607.18   679.2  606.07   691.7  610.43   709.7   621.8
   719.8   626.3   729.9  628.17   740.1  628.72   750.2  632.87   770.5  647.94
   780.5  653.08   820.5  669.31   900.6  707.85  1010.7  768.23  1070.7  787.19
#Mann= 3 , 0 , 0
    10.1     .06       0   666.7    .045       0   691.7     .06       0
#XS Ineff= 2 , 0
          625.89  721.79
Permanent Ineff=
       F       F
Bank Sta=666.7,691.7
XS Rating Curve= 0 ,0
Exp/Cntr=0.3,0.1

Type RM Length L Ch R = 1 ,15254.2 ,186.6,186.1,185.5
XS GIS Cut Line= 4
     1527252.927      391362.162     1527285.262      391720.158
     1527289.882      392025.032     1527333.765      392422.292
#Sta/Elev= 30
      10  805.44    39.9  800.52    69.9  793.19   119.8  786.02   129.8  783.16
   139.8  777.81   199.7  734.48   239.6  707.78   379.8  624.49   389.9  618.82
   400.1  615.25   542.4   614.8   552.6  613.96   580.7  606.74   593.2  606.02
   605.7  610.98   623.7  620.34   633.9   623.8   654.2   626.6   664.4   629.5
   674.4  634.64   704.3  652.67   754.3  679.59   844.2  736.49   864.2  747.33
   894.2  760.81   924.2  769.07   984.1  780.54  1014.1  783.59    1064  784.64
#Mann= 3 , 0 , 0
      10     .06       0   580.7    .045       0   605.7     .06       0
#XS Ineff= 2 , 0
          531.47  699.82
Permanent Ineff=
       F       F
Bank Sta=580.7,605.7
XS Rating Curve= 0 ,0
Exp/Cntr=0.3,0.1

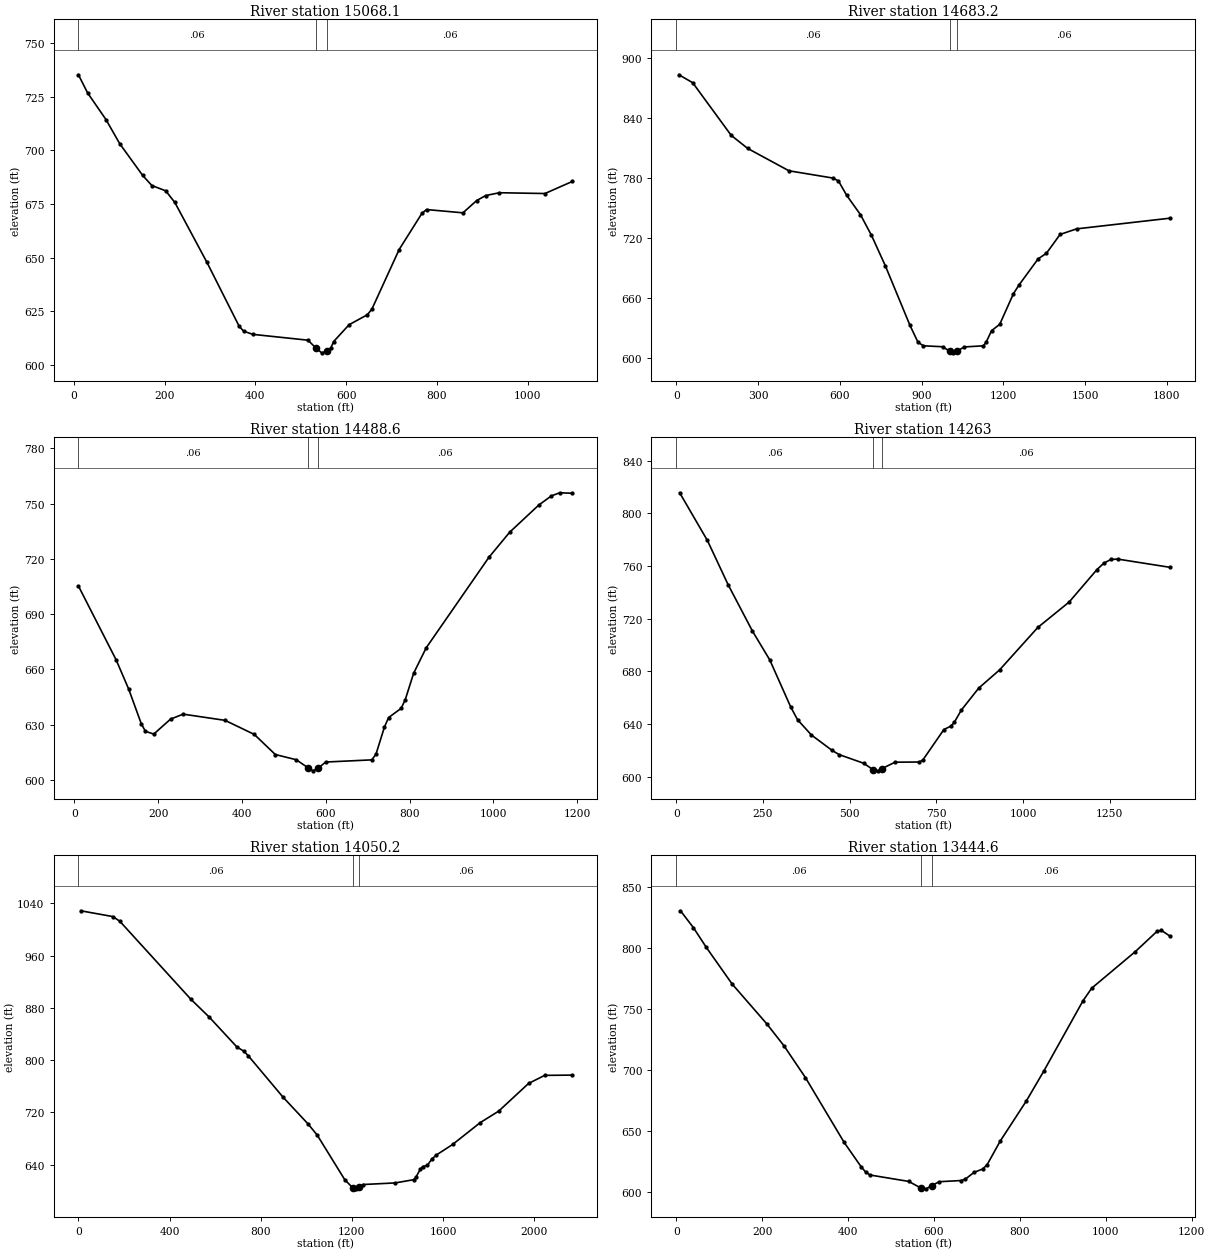
Type RM Length L Ch R = 1 ,15068.1 ,380.9,384.9,389
XS GIS Cut Line= 3
      1527103.18      391390.415     1527102.055      391916.656
     1527124.357      392488.538
#Sta/Elev= 30
    10.1  735.15    30.4  726.68    70.8   714.3   101.2  703.03   151.8  688.25
     172  683.57   202.4  681.12   222.6  675.69   293.5  647.74   364.3  618.05
   374.4  615.71   394.7  614.26  516.04  611.55   533.8  607.85   546.3  605.66
   558.8  606.44   566.4  607.95   572.6  610.92   606.6  618.75   646.7  623.37
   656.8  625.97     717  653.78   767.2  670.63   777.3  672.39   857.6  670.86
   887.7  676.57   907.8  678.91   937.9  680.22  1038.3  679.85  1098.6  685.47
#Mann= 3 , 0 , 0
    10.1     .06       0   533.8    .045       0   558.8     .06       0
Bank Sta=533.8,558.8
XS Rating Curve= 0 ,0
Exp/Cntr=0.3,0.1

Type RM Length L Ch R = 1 ,14683.2 ,197.2,194.6,192
XS GIS Cut Line= 4
     1526777.824      390859.381      1526749.63      391655.862
      1526700.29      392092.869     1527017.473      392572.167
#Sta/Elev= 30
    10.1  883.49    60.5  875.54   201.8   822.8   262.3   809.7   413.6  787.33
     575  780.04   595.2  777.15   625.5  762.67   675.9  743.38   716.3  722.65
   766.7  692.46   856.9  632.87   886.9  615.57   906.9  612.04   976.9   611.1
  1004.4  606.42  1016.9  604.99  1029.4  606.57  1056.9   610.9  1126.8  612.02
  1136.8   615.6  1156.8  627.18  1186.8  633.59  1236.8  664.14  1256.9  672.76
  1327.5  699.11  1357.8  704.67  1408.2  723.59  1468.7  729.16  1811.5  739.87
#Mann= 3 , 0 , 0
       0     .06       0  1004.4    .045       0  1029.4     .06       0
Bank Sta=1004.4,1029.4
XS Rating Curve= 0 ,0
Exp/Cntr=0.3,0.1

Type RM Length L Ch R = 1 ,14488.6 ,247.1,225.5,203.9
XS GIS Cut Line= 4
     1526245.919      391362.162     1526543.864      391671.655
     1526536.935      392001.935     1526797.926      392341.454
#Sta/Elev= 30
      10  705.25    99.9  665.18   129.9  649.28   159.9   630.5   169.8  626.34
   189.8  624.86   229.8  632.97   259.8  635.67   359.7  632.31   429.6  624.66
   479.7  613.75   529.7  610.92   557.3  606.61  569.72  604.89   582.3  606.37
   599.8  609.67   709.9  610.85   719.9  613.97   739.9  628.59   749.9  633.81
   779.9  638.82   789.8  643.62   809.7  657.89   839.6  671.67     989  720.75
  1038.8  734.46  1108.5  749.26  1138.4  754.19  1158.3  755.87  1188.2  755.61
#Mann= 3 , 0 , 0
      10     .06       0   557.3    .045       0   582.3     .06       0
Bank Sta=557.3,582.3
XS Rating Curve= 0 ,0
Exp/Cntr=0.3,0.1

Type RM Length L Ch R = 1 ,14263   ,230,212.9,195.7
XS GIS Cut Line= 4
      1525973.38       391440.69     1526252.848      391805.615
     1526467.645      392031.961     1526915.718       392505.44
#Sta/Elev= 30
      10  815.75    89.9  779.52   149.9  745.75   219.8  710.59   269.8  688.63
   329.7  653.12   349.7  643.24   389.7  631.58   449.7   619.8   469.7  616.67
   540.2   610.1   567.9  605.15   580.4  604.32   592.9     606   630.8  610.89
   701.2  611.04   711.3  612.68   771.7  635.75   791.7  638.31   801.8  641.26
   821.8  650.47     872  667.22   932.2  681.07  1042.5  713.38  1132.7  732.68
    1213  757.39    1233  762.29  1253.1  765.08  1273.1  765.31  1423.6  759.06
#Mann= 3 , 0 , 0
       0     .06       0   567.9    .045       0   592.9     .06       0
Bank Sta=567.9,592.9
XS Rating Curve= 0 ,0
Exp/Cntr=0.3,0.1

Type RM Length L Ch R = 1 ,14050.2 ,608,605.6,603.3
XS GIS Cut Line= 4
      1525149.62      391395.067     1526009.537       391994.19
     1526502.932      392092.869     1526908.219       392556.99
#Sta/Elev= 30
    10.1 1028.67   151.2 1019.78   181.4 1012.69   493.8  893.05   574.4  865.72
   695.3  820.16   725.6   813.7   745.7  806.49   896.9  743.67  1007.7  702.25
    1048   685.1  1168.8  616.83  1206.6  603.49  1219.1  602.84  1231.6  606.02
  1249.3  609.45  1390.2   611.9  1470.7  616.81  1480.8  620.46  1500.9  633.24
    1511  636.91  1531.1  638.71  1551.2  648.55  1571.4  654.81  1642.1  670.77
  1763.3  704.23  1844.1  721.79  1975.5  764.26  2046.2  776.61  2167.4  777.02
#Mann= 3 , 0 , 0
       0     .06       0  1206.6    .045       0  1231.6     .06       0
Bank Sta=1206.6,1231.6
XS Rating Curve= 0 ,0
Exp/Cntr=0.3,0.1

Type RM Length L Ch R = 1 ,13444.6 ,90.2,92.4,94.4
XS GIS Cut Line= 3
     1525768.604      392531.834      1526326.72      392593.312
     1526910.529      392664.456
#Sta/Elev= 30
      10  830.23    40.1  816.42    70.2  800.21   130.3  770.25   210.6  737.79
   250.7  719.81   300.8  693.71     391  640.62   431.1   620.4   441.2  616.35
   451.2  613.96   541.4  608.71   569.3  603.33   581.8  602.64   594.3  605.18
   612.2  608.47   662.9  609.44     673  610.58   693.3  616.12   713.6   618.9
   723.7  622.37   754.2  641.71     815  674.56   855.6  698.97   946.8  756.48
   967.1  766.85  1068.5  796.75  1119.2  813.39  1129.3  814.23  1149.6   809.4
#Mann= 3 , 0 , 0
       0     .06       0   569.3    .045       0   594.3     .06       0
Bank Sta=569.3,594.3
XS Rating Curve= 0 ,0
Exp/Cntr=0.3,0.1

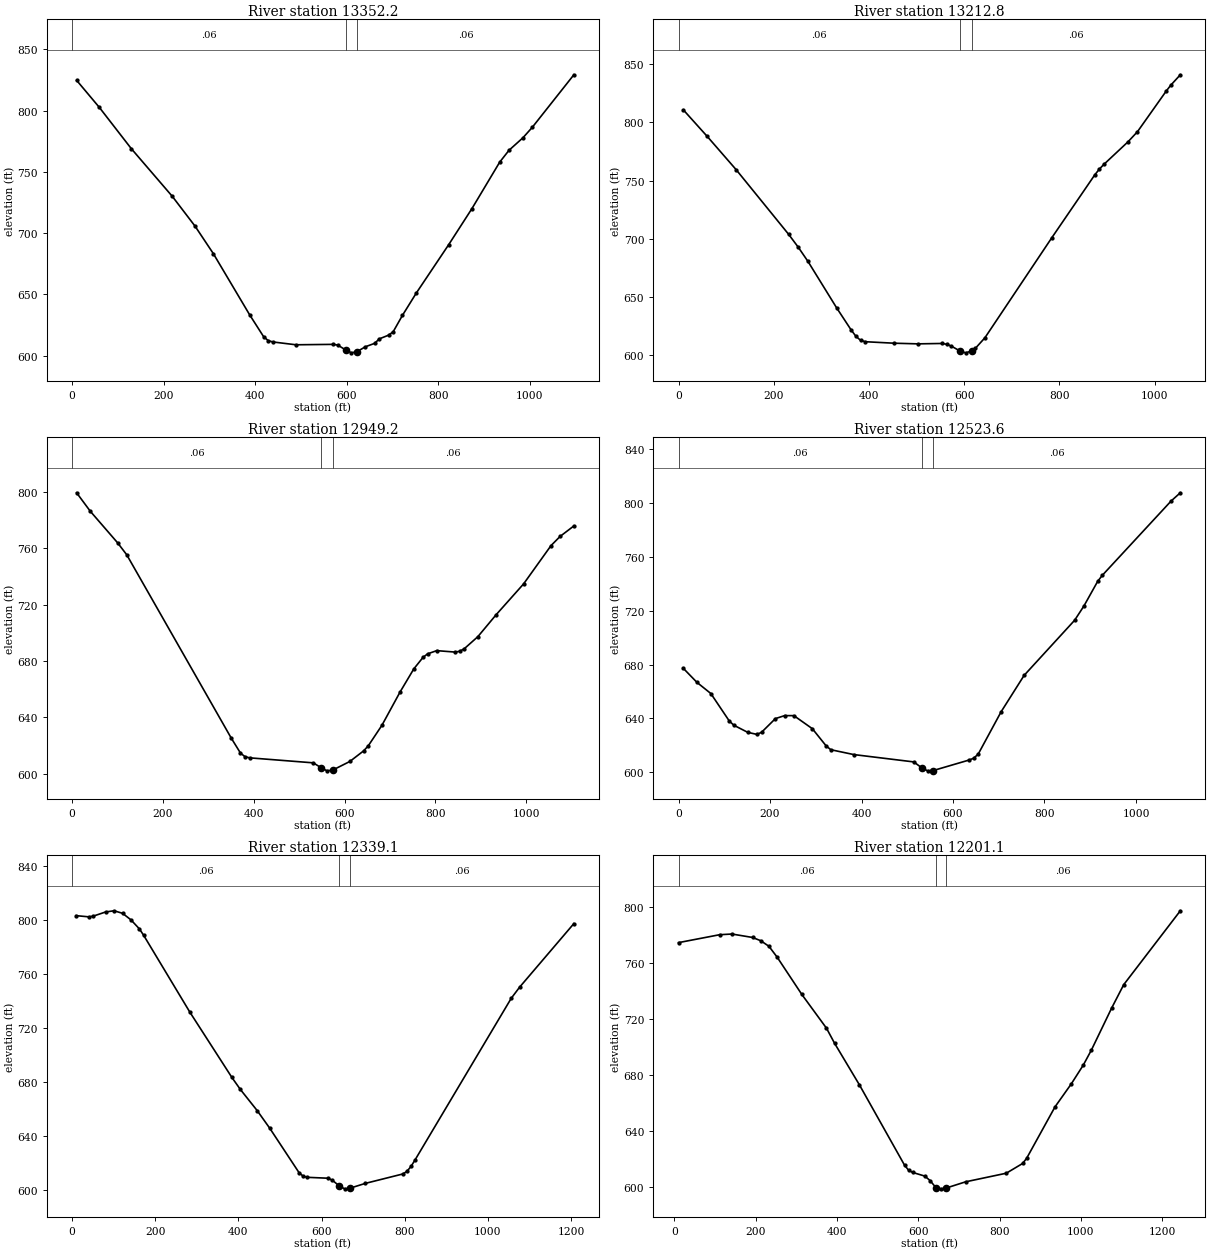
Type RM Length L Ch R = 1 ,13352.2 ,134.5,139.4,144.4
XS GIS Cut Line= 4
     1525767.821      392558.562     1526158.152       392637.09
     1526513.838      392715.618     1526825.641       392835.72
#Sta/Elev= 30
      10  824.76    59.7  802.64   129.4  769.04     219  730.11   268.8  705.74
   308.6  683.41   388.2  633.32   418.4  615.66   428.5  612.38   438.6  611.27
   489.2  608.96   570.2  609.29   580.3  608.77   598.1  604.69   610.6  602.38
   623.1  603.44     641  607.35   661.2  610.13   671.3  613.77   691.6   616.8
   701.7   619.6   721.9  632.95   752.3  651.24   823.2  690.79   873.8  720.11
   934.5  758.05   954.8   767.7   985.2   777.9  1005.4  786.33  1096.5  829.32
#Mann= 3 , 0 , 0
       0     .06       0   598.1    .045       0   623.1     .06       0
Bank Sta=598.1,623.1
XS Rating Curve= 0 ,0
Exp/Cntr=0.3,0.1

Type RM Length L Ch R = 1 ,13212.8 ,255.2,263.6,272
XS GIS Cut Line= 4
     1525786.298      392590.897     1526132.746      392727.166
     1526446.858      392861.126     1526758.662      392997.396
#Sta/Elev= 30
    10.1   810.7    60.4  787.85   120.7   759.5   231.4  703.78   251.5  692.76
   271.7  680.69     332  640.77   362.2  621.96   372.3  616.43   382.3  612.83
   392.4  611.64   452.6  610.36   502.9   609.8   553.1  610.14   563.1  609.46
   573.2  607.84   590.8  603.74   603.3  602.09   615.8  603.71   623.4  605.92
   643.5     615   783.8  700.77   873.9  754.66   883.9  759.84   893.9  764.08
     944  783.23     964  791.97    1024  826.63    1034   831.9    1054  840.83
#Mann= 3 , 0 , 0
       0     .06       0   590.8    .045       0   615.8     .06       0
Bank Sta=590.8,615.8
XS Rating Curve= 0 ,0
Exp/Cntr=0.3,0.1

Type RM Length L Ch R = 1 ,12949.2 ,427.6,425.5,423.3
XS GIS Cut Line= 3
     1525725.635      392660.123     1526143.459      392988.028
     1526582.431       393357.35
#Sta/Elev= 30
      10  799.51    40.1  786.39   100.2  763.98   120.3  755.48   350.7  625.04
   370.8  614.53   380.8  611.95   390.8  611.15   531.1  607.59   548.8  604.03
   561.3  601.91   573.8  602.44   611.6  608.57   641.8  616.08   651.9  619.57
   682.1  634.21   722.4  658.07   752.5   674.4   772.7  682.54   782.7  685.04
   802.9  687.33   843.1  686.31   853.2  686.84   863.3  688.62   893.4  697.25
   933.7  712.86   994.1  734.74  1054.5  761.97  1074.6  768.52  1104.8  775.94
#Mann= 3 , 0 , 0
       0     .06       0   548.8    .045       0   573.8     .06       0
Bank Sta=548.8,573.8
XS Rating Curve= 0 ,0
Exp/Cntr=0.3,0.1

Type RM Length L Ch R = 1 ,12523.6 ,191.7,184.6,177.5
XS GIS Cut Line= 3
     1525417.192      392981.499       1525859.9      393298.739
     1526310.116      393618.767
#Sta/Elev= 30
    10.1  677.36    40.3   666.8    70.6  658.54   110.9  638.15     121  634.97
   151.3  629.71   171.5  628.18   181.5  629.75   211.8  639.92     232  642.13
   252.1  642.12   292.5  632.43   322.7  619.66   332.8  616.82   383.3   613.2
   514.4  607.75   532.1  603.24   544.6  601.13   557.1  601.38     635  609.13
   645.1  610.46   655.1  613.53   705.3  645.03   755.5     672     866  712.96
   886.1  723.44   916.2  741.75   926.3  746.24  1076.9  801.48    1097  807.58
#Mann= 3 , 0 , 0
       0     .06       0   532.1    .045       0   557.1     .06       0
Bank Sta=532.1,557.1
XS Rating Curve= 0 ,0
Exp/Cntr=0.3,0.1

Type RM Length L Ch R = 1 ,12339.1 ,138.3,138,137.7
XS GIS Cut Line= 4
     1525144.214      393228.361     1525629.241      393403.895
     1525917.948      393514.758     1526266.705      393669.505
#Sta/Elev= 30
    10.1  802.97    40.5  802.09    50.6  802.58    80.9  805.73   101.1  806.59
   121.4  804.72   141.6  799.86   161.8  793.21   171.9  788.54   283.2   731.5
   384.3   683.1   404.6  674.24     445  658.59   475.4  645.45   545.7   612.6
   555.7  609.92   565.7   609.1   615.6  608.44   625.6  606.98     643  602.66
   655.5  600.57     668  601.03   705.4  604.63   795.1  611.57   805.1  613.49
   815.1  617.21   825.1  622.18    1056  741.74  1076.1  749.97  1206.6  797.09
#Mann= 3 , 0 , 0
       0     .06       0     643    .045       0     668     .06       0
Bank Sta=643,668
XS Rating Curve= 0 ,0
Exp/Cntr=0.3,0.1

Type RM Length L Ch R = 1 ,12201.1 ,162.4,157,151.7
XS GIS Cut Line= 4
     1525065.686      393371.559     1525596.906      393535.545
     1525915.638      393655.647     1526255.157      393731.865
#Sta/Elev= 30
    10.1  774.34   111.2  779.97   141.5  780.46   192.1  778.02   212.3   775.7
   232.5  771.72   252.7  763.98   313.4  737.43     374  713.41   394.2  702.53
   454.9  673.12     566  615.87     576  612.25     586  610.67  616.05  608.04
  628.86  604.87   643.6  599.74   656.1  598.98   668.6  599.57  716.45  603.99
   816.4  610.11   856.5  617.04   866.5  620.76   936.3   657.4   976.1  673.66
  1005.9  687.17  1025.8  697.86  1075.5   727.7  1105.3  744.42  1244.5  797.02
#Mann= 3 , 0 , 0
    10.1     .06       0   643.6    .045       0   668.6     .06       0
Bank Sta=643.6,668.6
XS Rating Curve= 0 ,0
Exp/Cntr=0.3,0.1