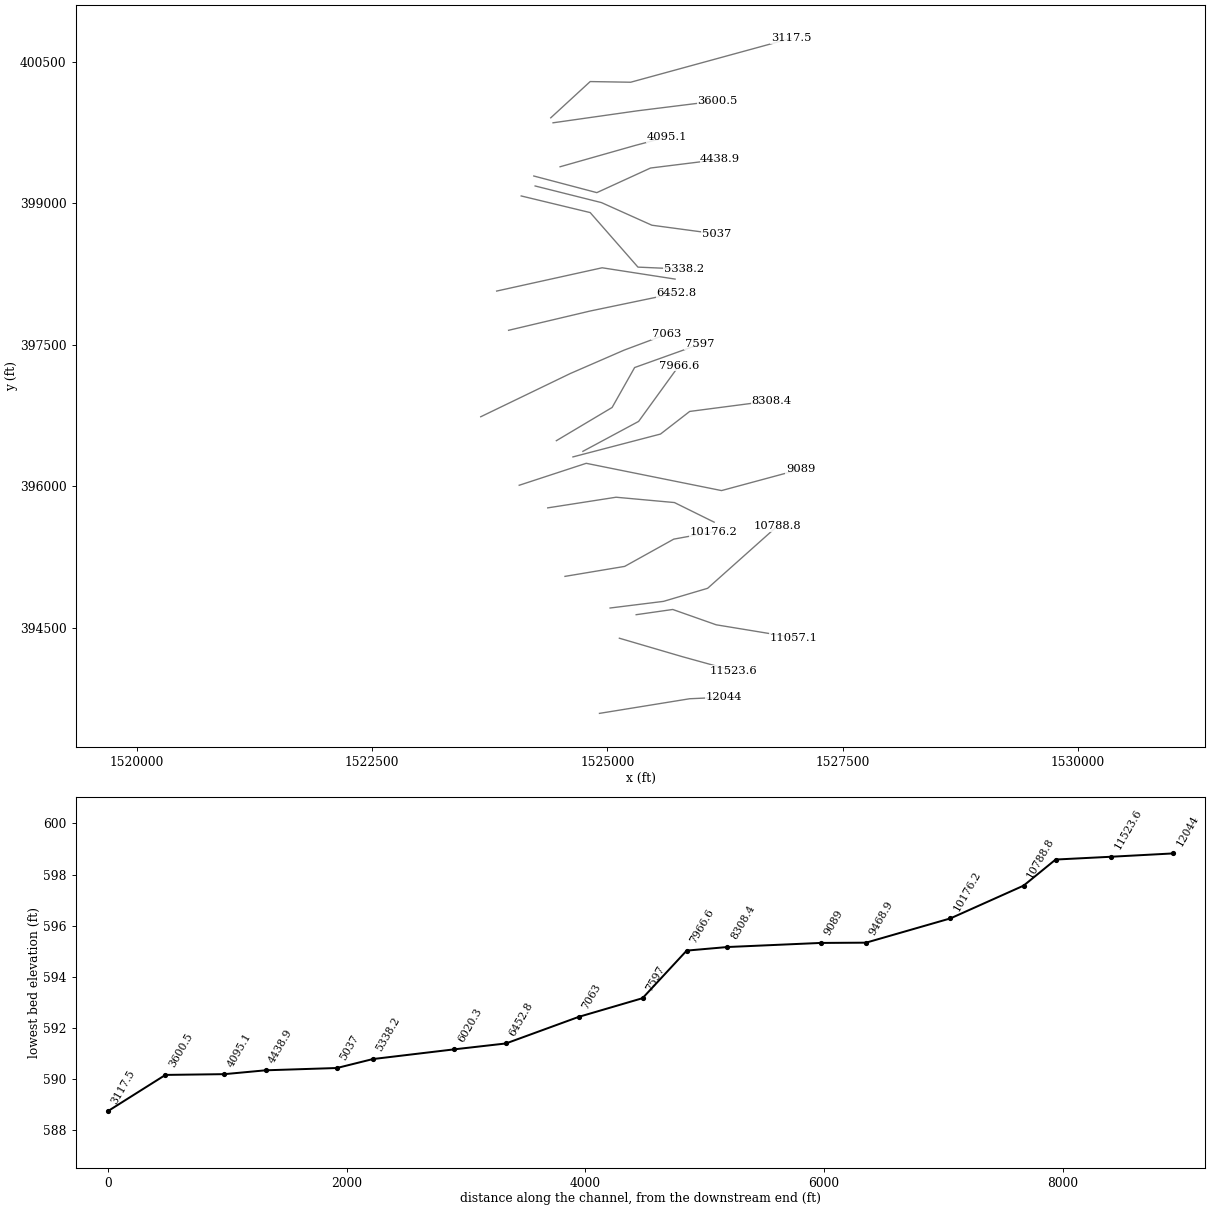
HEC-RAS study MILLCR.prj: MILLCR

--- MILLCR.g01 (geometry) --- (continued)

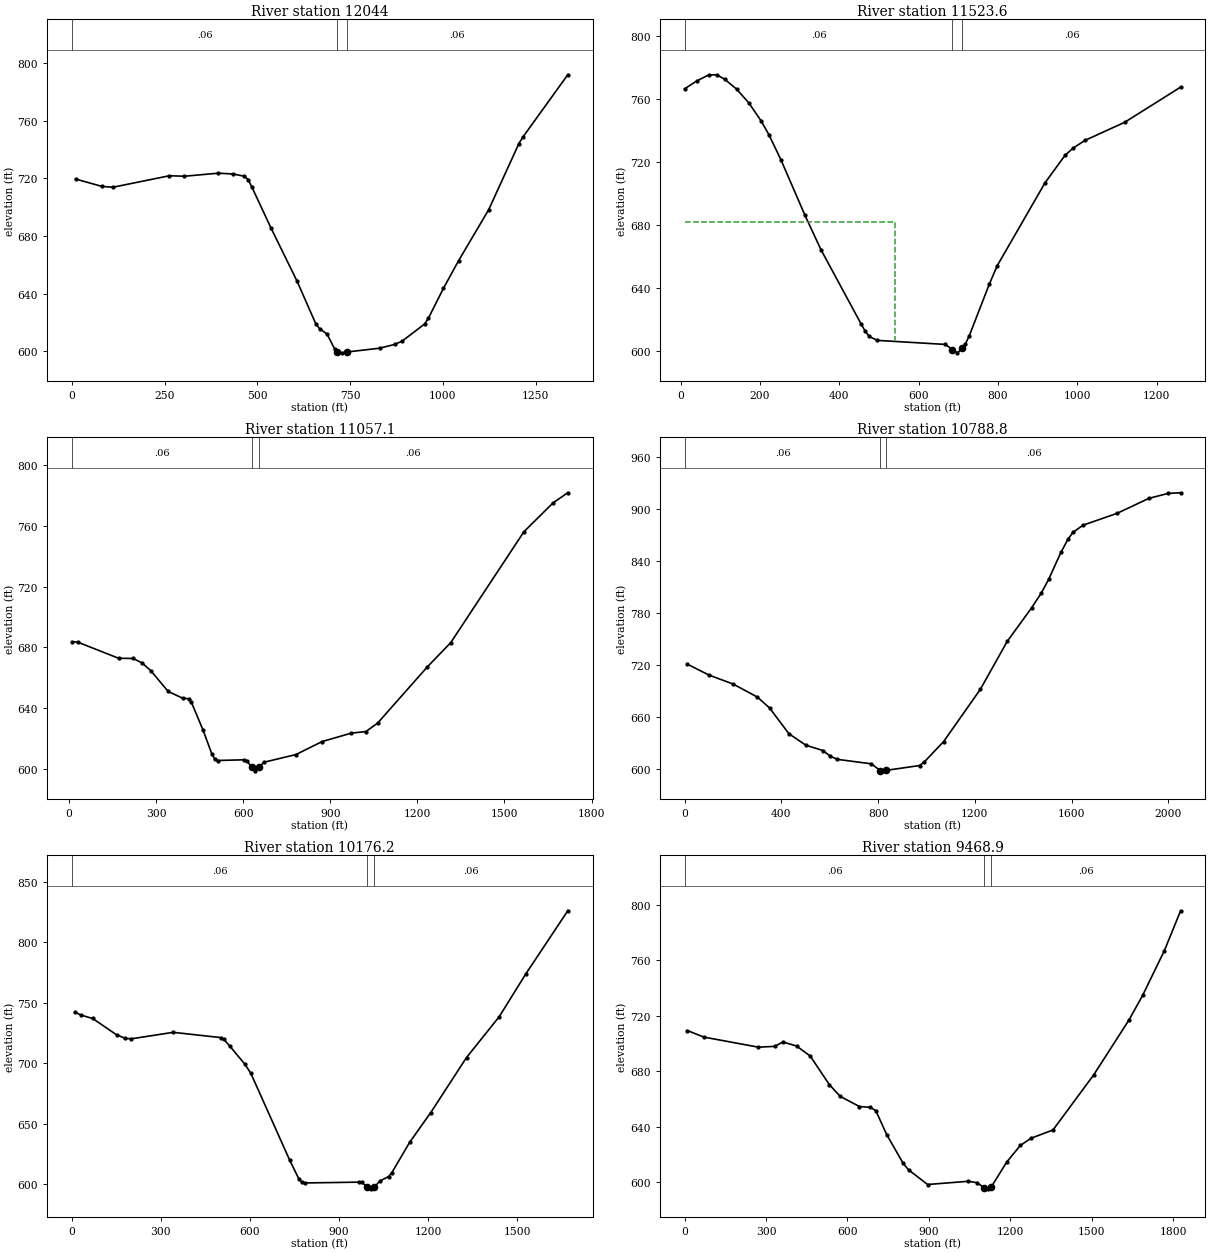
Type RM Length L Ch R = 1 ,12044   ,532.9,520.4,508.4
XS GIS Cut Line= 3
      1524917.02        393594.2     1525875.616      393749.266
     1526240.586      393765.436
#Sta/Elev= 30
    10.1  719.63    80.9  714.49   111.3  713.92     263  721.89   303.5  721.55
   394.5  723.66     435  723.12   465.3  721.51   475.4  719.06   485.5   713.9
   536.1  685.92   606.9   648.7   657.5  618.97   667.6  615.64   687.8   611.9
   708.1  601.58   715.8   599.7   728.3  598.83   740.8   599.4   829.4  602.05
   869.9  604.67   890.1  606.96   950.8   618.9   960.9   622.9  1001.5   643.7
  1042.1   662.8  1123.3  698.28  1204.5  744.11  1214.6  748.48  1336.4  792.05
#Mann= 3 , 0 , 0
       0     .06       0   715.8    .045       0   740.8     .06       0
Bank Sta=715.8,740.8
XS Rating Curve= 0 ,0
Exp/Cntr=0.3,0.1

Type RM Length L Ch R = 1 ,11523.6 ,469,466.6,463.7
XS GIS Cut Line= 3
     1525128.475       394390.68     1525798.297      394194.821
     1526340.817      394045.304
#Sta/Elev= 30
    10.1  766.52    40.5  771.52    70.8  775.35      91  775.45   111.3  772.59
   141.6  766.22   171.9  757.59   202.3  746.38   222.5   737.4   252.9  721.41
   313.5  686.13     354  664.18   455.1  617.03   465.2  612.52   475.4  609.13
   495.6  606.62   667.5  604.05   685.4  600.78  697.85   598.7   710.4  601.55
     718  604.33     728  609.69   778.3  642.39   798.4  654.17   918.9  706.85
   969.2  724.24   989.3  728.78  1019.4  733.73  1119.9  745.29  1260.6  767.61
#Mann= 3 , 0 , 0
    10.1     .06       0   685.4    .045       0   710.4     .06       0
#XS Ineff= 2 , 0
           540.1  681.87
Permanent Ineff=
       F       F
Bank Sta=685.4,710.4
XS Rating Curve= 0 ,0
Exp/Cntr=0.3,0.1

Type RM Length L Ch R = 1 ,11057.1 ,250.7,268.2,285.8
XS GIS Cut Line= 4
      1525306.92      394639.999     1525695.355      394695.351
     1526157.286      394532.954      1526982.23      394397.729
#Sta/Elev= 30
    10.1  683.67    30.2  683.45     171  672.81   221.3  672.64   251.5  669.79
   281.7   664.7   342.1  650.91   392.4  646.42   412.3  646.14   422.3  643.67
   462.3  625.36   492.3  609.76   502.3  606.48   512.3   605.4   602.2  605.87
   612.2   605.4   629.7  600.92  641.91  598.59   654.7   601.1   672.2  604.27
   782.1  609.33     872  617.88   972.7  623.44    1023  624.49  1063.3  630.06
  1234.5  667.12  1315.1   683.1  1566.9  756.16  1667.6  775.24    1718  781.86
#Mann= 3 , 0 , 0
    10.1     .06       0   629.7    .045       0   654.7     .06       0
Bank Sta=629.7,654.7
XS Rating Curve= 0 ,0
Exp/Cntr=0.3,0.1

Type RM Length L Ch R = 1 ,10788.8 ,606.4,612.6,618.8
XS GIS Cut Line= 4
     1525029.796       394710.89     1525597.484      394781.314
     1526066.343      394919.893     1526806.018      395577.855
#Sta/Elev= 30
      10  720.91   100.4  708.15   200.7  697.73   301.1  682.67   351.3  670.09
   431.5  640.33   501.8  627.09     572     621     602  614.51   631.9   610.8
   771.6   605.7     809  597.94   821.5  597.57     834  598.17   971.2  603.68
   991.1  607.86  1071.1  631.41  1222.6  691.58  1333.7  746.91  1434.7  785.69
  1475.1   802.9  1505.4  818.72  1555.9  849.67  1586.2  865.47  1606.4  872.93
  1646.8  881.04  1788.3  894.81  1919.6  912.08  2000.4  917.89  2050.9  918.53
#Mann= 3 , 0 , 0
       0     .06       0     809    .045       0     834     .06       0
Bank Sta=809,834
XS Rating Curve= 0 ,0
Exp/Cntr=0.3,0.1

Type RM Length L Ch R = 1 ,10176.2 ,719,707.4,695.7
XS GIS Cut Line= 4
     1524550.498      395046.191     1525184.863      395151.918
     1525706.452      395440.907     1526130.838      395518.183
#Sta/Elev= 30
      10  742.58    30.1     740    70.3  737.14   150.7  723.65   180.9  720.66
     201  720.34   341.7  725.68   502.4  721.33   512.5  719.76   532.6  714.22
   582.8  699.39   602.9  691.95   734.1  619.97   764.4  604.76   774.5  601.97
   784.6  601.15   966.5  601.82   976.6   601.6   994.5  598.07    1007  596.29
  1019.5  597.77  1037.3  602.69  1067.6  606.49  1077.7  609.47  1138.3  634.79
  1209.1  659.29  1329.7  704.86    1440  738.66  1530.3  774.31  1670.8  826.18
#Mann= 3 , 0 , 0
       0     .06       0   994.5    .045       0  1019.5     .06       0
Bank Sta=994.5,1019.5
XS Rating Curve= 0 ,0
Exp/Cntr=0.3,0.1

Type RM Length L Ch R = 1 ,9468.9  ,347.7,379.9,385.6
XS GIS Cut Line= 4
     1524367.237      395772.186     1525093.232      395884.962
       1525713.5      395828.574     1526135.442      395620.653
#Sta/Elev= 30
    10.1  709.36    70.5  704.65   271.7  697.38   332.1  697.95   362.3  701.15
   412.6   698.2     463  690.97   533.4  670.37   573.7  661.89   644.1  654.64
   684.4  654.03   704.5  651.69   744.7  634.41     805  613.81   825.1  609.06
   895.4  598.46  1046.1  600.79  1076.3   599.8  1103.9  596.27  1116.4  595.34
  1128.9  596.32  1186.8  614.58    1237  626.57  1277.2  631.84  1357.5  637.72
  1507.7  677.45  1637.8  717.02  1687.8  734.63  1767.9  766.83  1827.9  795.61
#Mann= 3 , 0 , 0
       0     .06       0  1103.9    .045       0  1128.9     .06       0
Bank Sta=1103.9,1128.9
XS Rating Curve= 0 ,0
Exp/Cntr=0.3,0.1

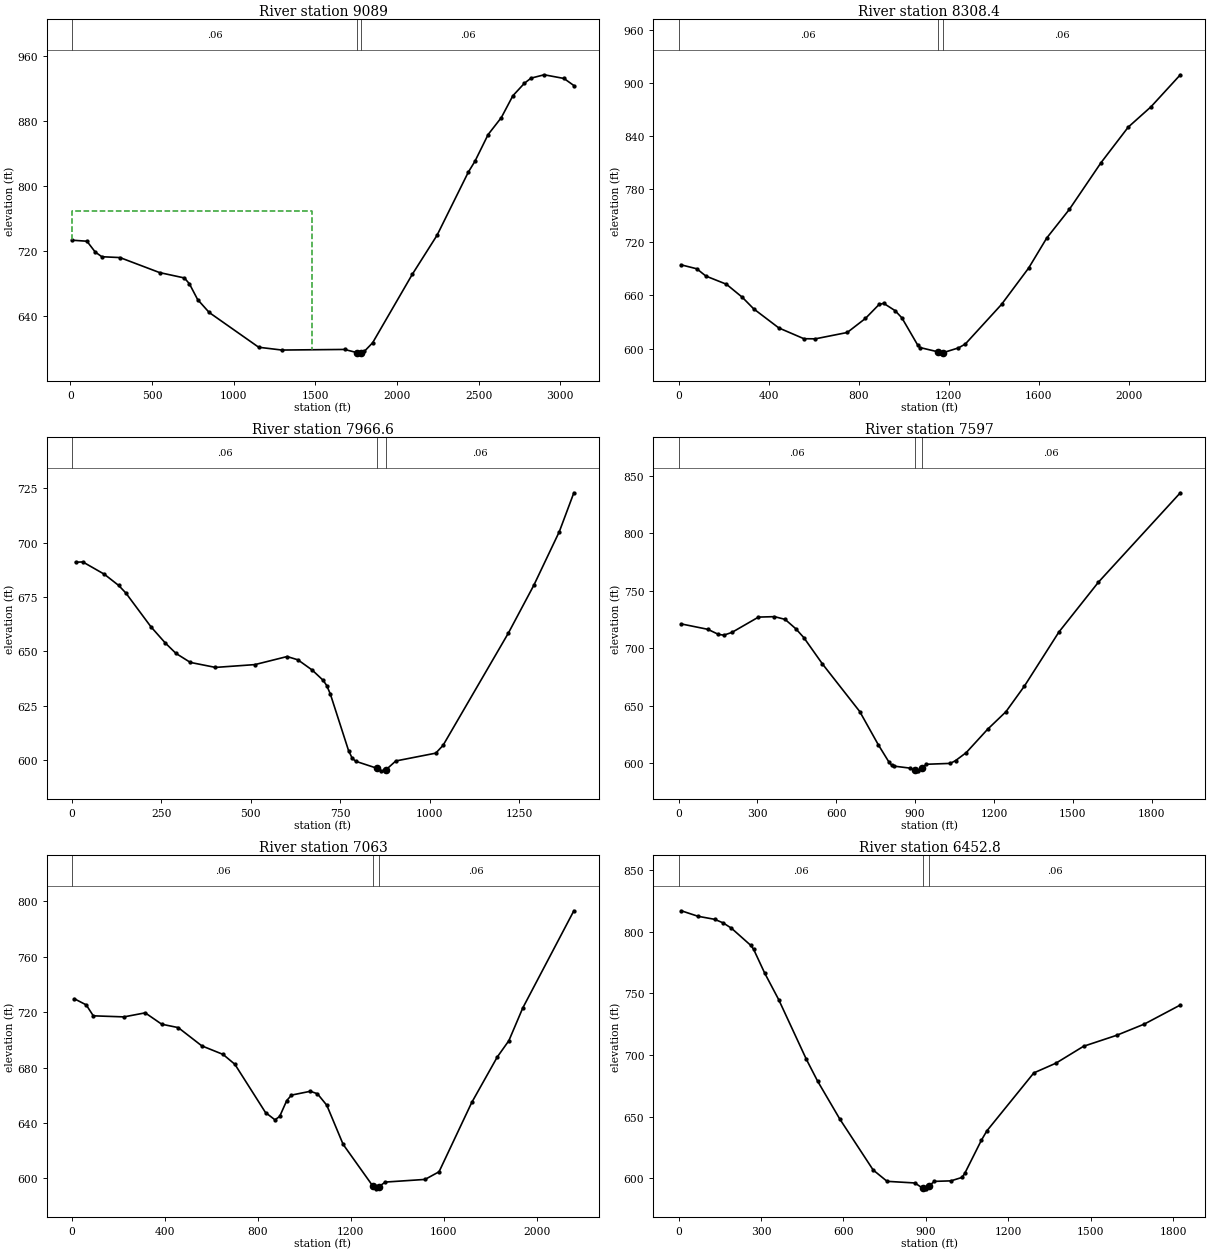
Type RM Length L Ch R = 1 ,9089    ,799.1,780.6,788.6
XS GIS Cut Line= 4
     1524064.151      396011.835      1524776.05      396244.436
     1526213.944      395955.447     1527052.715      396180.999
#Sta/Elev= 30
    10.1  733.78   101.2  732.53   151.8  719.28   192.3  713.47   303.6  712.43
   546.5  693.97   698.3  687.37   728.7  680.26   779.3  660.85   850.1  644.95
  1153.5   602.2  1295.1  598.76  1679.5   599.5    1758  595.45  1770.5  595.33
    1783  595.62  1800.9   597.2  1851.4  607.71  2094.2  691.76  2245.9  739.79
  2437.8  817.53  2478.2  830.79    2559  863.67  2639.8  884.49  2710.5  911.32
  2781.2  926.69  2821.6  932.96  2902.4  937.12  3023.6   932.6  3084.2  923.89
#Mann= 3 , 0 , 0
    10.1     .06       0    1758    .045       0    1783     .06       0
#XS Ineff= 2 , 0
         1479.06  769.78
Permanent Ineff=
       F       F
Bank Sta=1758,1783
XS Rating Curve= 0 ,0
Exp/Cntr=0.3,0.1

Type RM Length L Ch R = 1 ,8308.4  ,331.9,341.8,352.2
XS GIS Cut Line= 4
      1524635.08      396312.278     1525565.482       396554.57
     1525875.616      396794.219     1526742.581      396906.995
#Sta/Elev= 30
    10.1  694.56      81  690.02   121.4  681.81   212.5  672.59   283.4  657.79
     334  644.72   445.3  623.25   556.6  611.11   607.2  610.97   748.9  618.13
   829.9  634.04   890.6  649.84   910.8  651.02   961.4  642.77   991.6  634.61
  1061.9  603.85    1072  601.13  1149.9  596.41  1162.4  595.17  1174.9  595.39
  1242.8  600.74    1273   605.1  1433.8  649.79  1554.4  690.91  1634.7  724.79
  1735.2  757.13  1875.9  809.89  1996.5  849.92    2097  872.73  2227.6  908.94
#Mann= 3 , 0 , 0
       0     .06       0  1149.9    .045       0  1174.9     .06       0
Bank Sta=1149.9,1174.9
XS Rating Curve= 0 ,0
Exp/Cntr=0.3,0.1

Type RM Length L Ch R = 1 ,7966.6  ,364.6,369.6,373.5
XS GIS Cut Line= 3
     1524740.807      396371.309     1525332.881      396688.491
      1525762.84      397280.565
#Sta/Elev= 30
      10  690.99    30.1  691.11    90.2  685.46   130.3  680.31   150.4  676.83
   220.6  661.28   260.7  653.84   290.7  649.03   330.8   644.9     401   642.6
   511.3  643.89   601.5   647.6   631.6  646.09   671.7  641.37   702.2  636.67
   712.3  634.24   722.5  630.27   773.3  604.33   783.5  600.82   793.6  599.41
   852.3  596.24   864.8  595.03   877.3  595.43   905.4  599.57  1017.2  603.17
  1037.5  606.73  1220.5  658.47  1291.6  680.44  1362.8  705.07  1403.4  722.92
#Mann= 3 , 0 , 0
       0     .06       0   852.3    .045       0   877.3     .06       0
Bank Sta=852.3,877.3
XS Rating Curve= 0 ,0
Exp/Cntr=0.3,0.1

Type RM Length L Ch R = 1 ,7597    ,552,534,516.9
XS GIS Cut Line= 4
     1524458.867      396484.085     1525051.355      396836.276
      1525290.59       397259.42     1525981.343      397506.117
#Sta/Elev= 30
    10.1  721.09   111.5  716.39     152  711.94   172.3  711.31   202.7  713.66
   304.1  727.03   364.9  727.42   405.4  725.03     446   716.9   476.4  709.23
   547.4  686.24   689.3   644.8   760.1   615.8   800.7   600.7   810.8  598.07
   820.9  597.24   881.7   595.5   899.6  593.73   912.1  593.17   924.6  595.34
   942.4  598.89  1033.6  599.65  1053.8  602.07  1094.3  609.01  1175.4  629.29
  1245.7  644.72    1316  667.05  1446.6  713.93  1597.4  757.47  1908.8  835.27
#Mann= 3 , 0 , 0
       0     .06       0   899.6    .045       0   924.6     .06       0
Bank Sta=899.6,924.6
XS Rating Curve= 0 ,0
Exp/Cntr=0.3,0.1

Type RM Length L Ch R = 1 ,7063    ,615.7,610.3,602.4
XS GIS Cut Line= 4
     1523655.338      396737.831     1524606.886      397195.983
     1525179.595      397444.256     1525628.918      397611.845
#Sta/Elev= 30
    10.2  729.59    60.9  725.22    91.4  717.32   223.4  716.55   314.8  719.47
   385.9  711.26     457  708.82   558.5  695.63   649.9  689.47   700.7  682.35
   832.7   647.5   873.3  642.26   893.6  644.69   924.1  656.18   944.4  660.09
  1025.6  662.86  1056.1  661.07  1096.4  652.79  1166.8  624.52  1295.3  594.28
  1307.8  592.44  1320.3  593.98  1348.1  597.32  1519.2  599.24  1579.6  604.75
  1720.3  654.76  1830.2  687.59  1880.1  699.37  1940.1  723.03  2159.9  793.14
#Mann= 3 , 0 , 0
       0     .06       0  1295.3    .045       0  1320.3     .06       0
Bank Sta=1295.3,1320.3
XS Rating Curve= 0 ,0
Exp/Cntr=0.3,0.1

Type RM Length L Ch R = 1 ,6452.8  ,433.3,432.4,432.2
XS GIS Cut Line= 3
     1523951.375      397654.136     1524818.341      397858.542
     1525734.646      398048.852
#Sta/Elev= 30
    10.1  817.08    70.9  812.61   131.6  810.14     162  807.28   192.3     803
   263.2  788.95   273.3  785.82   313.8  766.41   364.4  745.05   465.6   696.4
   506.1  678.88   587.1  648.01   708.5  606.68   759.2  597.49   860.4  596.16
   888.3  591.98   900.8   591.4   913.3  594.01     931  597.46   991.4  597.87
  1031.6  600.65  1041.7  603.85  1102.1  630.71  1122.2   638.4  1293.3  685.49
  1373.8  693.39  1474.4  707.11  1595.1  716.03  1695.8  725.15  1826.6  740.61
#Mann= 3 , 0 , 0
       0     .06       0   888.3    .045       0   913.3     .06       0
Bank Sta=888.3,913.3
XS Rating Curve= 0 ,0
Exp/Cntr=0.3,0.1

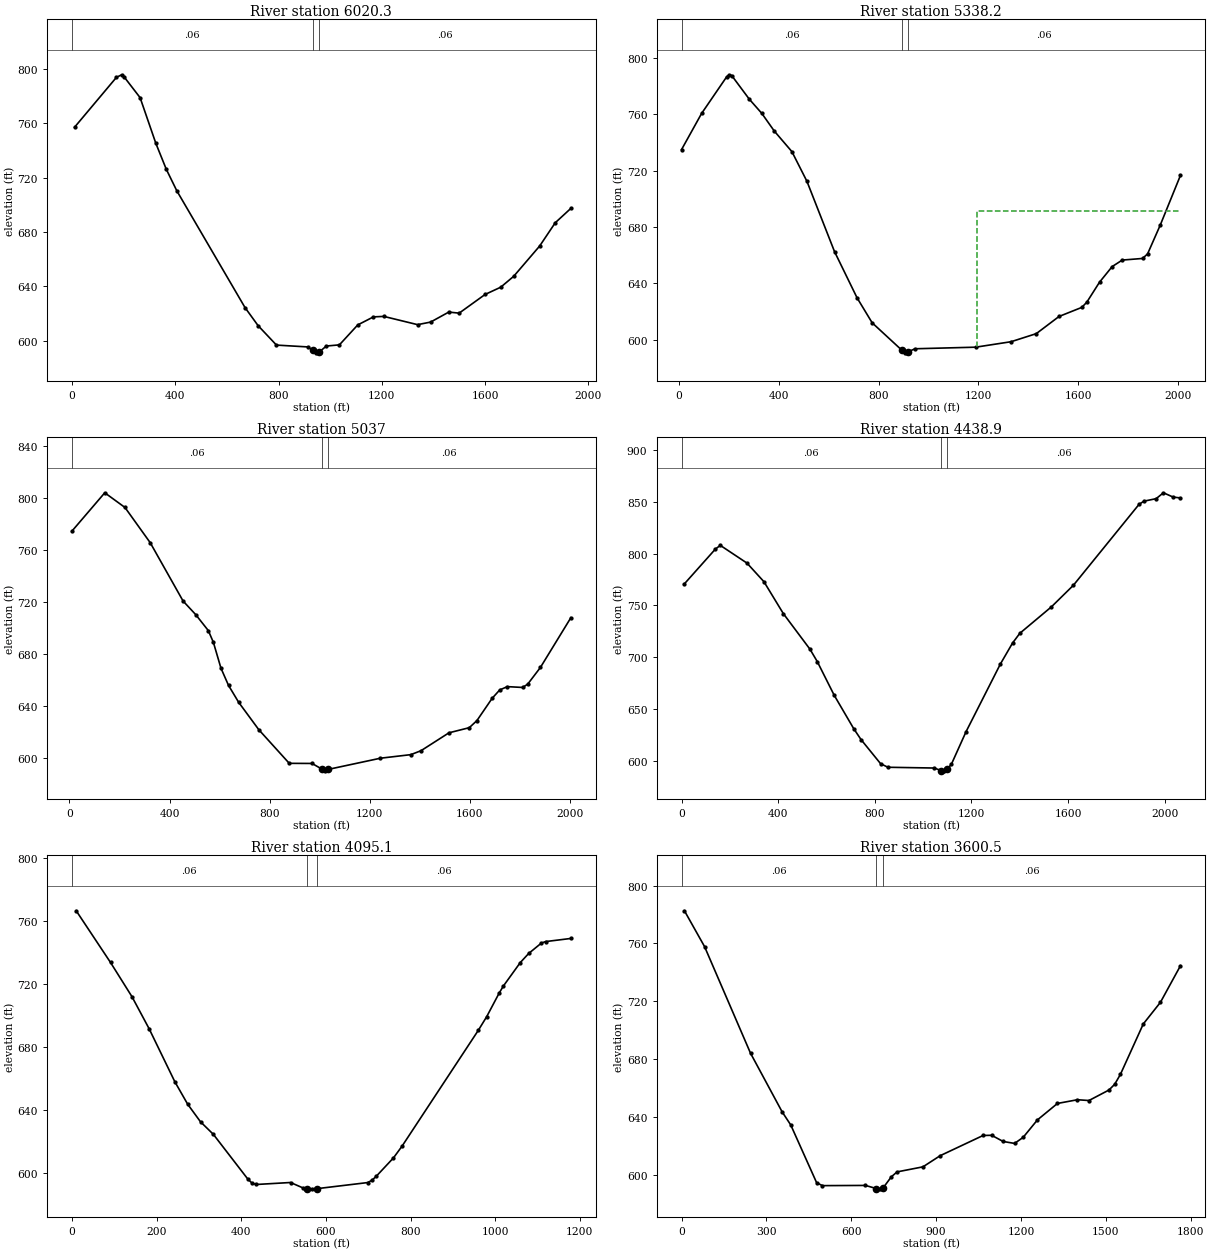
Type RM Length L Ch R = 1 ,6020.3  ,711.1,682.2,653.2
XS GIS Cut Line= 3
     1523824.502      398069.997     1524945.214      398316.695
     1525720.549       398196.87
#Sta/Elev= 30
    10.2  756.96   172.6  793.66   192.9   795.5   203.1   793.7     264  778.69
     325  745.11   365.6  725.99   406.2  710.23   670.2  624.46     721  611.14
   792.1  596.86     914  595.51   931.9  593.04   944.4  591.17   956.9  591.61
   985.1  596.17  1035.8  597.03  1106.9  611.69  1167.7   617.6  1207.9  617.94
  1338.6  611.88  1388.9  613.77  1459.3  621.11  1499.6  620.35  1600.2   634.1
  1660.5   639.4  1710.8  647.41  1811.4  669.69  1871.7  686.77  1932.1  697.32
#Mann= 3 , 0 , 0
       0     .06       0   931.9    .045       0   956.9     .06       0
Bank Sta=931.9,956.9
XS Rating Curve= 0 ,0
Exp/Cntr=0.3,0.1

Type RM Length L Ch R = 1 ,5338.2  ,287.4,301.2,318.4
XS GIS Cut Line= 4
     1524085.297      399077.933     1524818.341      398901.721
     1525325.833      398323.743     1525812.179      398302.598
#Sta/Elev= 30
    10.1  734.89    90.5   760.5     191  786.49     201  787.92   211.1   787.4
   281.5  770.66   331.7  760.57     382  747.99   452.4  733.45   512.7  712.39
   623.2  662.58   713.7  629.76   774.2  612.07   893.2  592.65  905.45  590.79
   918.2  591.57   946.2  593.68  1189.1   594.8  1330.8  598.67    1432   604.4
  1523.1  616.57  1614.4  623.01  1634.6  626.72  1685.4  640.86  1736.1  651.94
  1776.6  656.56  1857.8   657.7    1878  660.91  1928.8  681.33  2009.9  716.62
#Mann= 3 , 0 , 0
    10.1     .06       0   893.2    .045       0   918.2     .06       0
#XS Ineff= 2 , 0
                         1196.07          691.03
Permanent Ineff=
       F       F
Bank Sta=893.2,918.2
XS Rating Curve= 0 ,0
Exp/Cntr=0.3,0.1

Type RM Length L Ch R = 1 ,5037    ,575.3,598.1,616
XS GIS Cut Line= 4
     1524233.315      399183.661     1524938.165      399007.448
     1525473.851      398767.799     1526157.556      398676.169
#Sta/Elev= 30
    10.1  774.48   141.3  803.93     222  792.65   322.9  765.59   454.1  720.83
   504.5  710.41     555  698.11   575.2   689.1   605.5  669.24   635.7  656.03
   676.1  643.09   756.9  621.96   878.3   596.2   969.4  596.11  1007.5   591.9
 1019.86  590.44  1032.5  591.49  1242.6  600.14  1364.1  602.88  1404.7  605.91
  1516.3  619.64  1597.4  623.57  1627.9     629  1688.7   646.1  1719.2  652.59
  1749.6  655.09  1810.5  654.46  1830.8     657  1881.5  669.79  2003.2     708
#Mann= 3 , 0 , 0
    10.1     .06       0  1007.5    .045       0  1032.5     .06       0
Bank Sta=1007.5,1032.5
XS Rating Curve= 0 ,0
Exp/Cntr=0.3,0.1

Type RM Length L Ch R = 1 ,4438.9  ,347.6,343.8,339.9
XS GIS Cut Line= 4
     1524219.218      399289.388     1524888.826      399113.176
     1525459.754       399373.97     1526199.847      399465.601
#Sta/Elev= 30
      10  770.43   140.5  804.57   160.6  808.03   270.9  790.94   341.2  772.96
   421.5  742.16   531.8  707.77     562  695.85   632.2  663.26   712.7  631.15
     743  620.59     824   597.3   854.4   593.8  1046.7  593.06  1074.7   590.6
  1087.2  590.35  1099.7  591.76  1117.6  596.87  1178.3  628.29  1320.1  693.47
  1370.5  713.74  1400.7  723.15  1531.7  748.74  1622.4  769.51  1894.5  847.71
  1914.7  850.74    1965  853.14  1995.3  858.83  2035.6  854.65  2065.8  853.86
#Mann= 3 , 0 , 0
       0     .06       0  1074.7    .045       0  1099.7     .06       0
Bank Sta=1074.7,1099.7
XS Rating Curve= 0 ,0
Exp/Cntr=0.3,0.1

Type RM Length L Ch R = 1 ,4095.1  ,501.5,494.7,490.9
XS GIS Cut Line= 3
     1524498.554      399387.341     1525297.639      399613.619
     1525634.452      399702.502
#Sta/Elev= 30
    10.1  766.64    91.2  733.83   141.8  712.16   182.3  691.84   243.1  658.18
   273.5  643.89   303.8  632.74   334.2  624.77   415.3   596.5   425.4  593.84
   435.5  592.96   516.5  594.22   546.9  590.67   554.7  590.31   567.2   590.2
   579.7  590.34   698.8  594.18     709  595.68   719.1  598.19   759.6  609.81
   779.9  617.25   959.9  690.68   979.8  699.37  1009.7  714.55  1019.6  718.98
  1059.4   733.8  1079.3  739.58  1109.2  746.15  1119.1  747.09  1178.8  749.08
#Mann= 3 , 0 , 0
       0     .06       0   554.7    .045       0   579.7     .06       0
Bank Sta=554.7,579.7
XS Rating Curve= 0 ,0
Exp/Cntr=0.3,0.1

Type RM Length L Ch R = 1 ,3600.5  ,484.3,483,478.6
XS GIS Cut Line= 3
     1524423.625      399853.268     1525318.784      399980.141
     1526171.653      400085.869
#Sta/Elev= 30
    10.2  782.58    81.3  757.81   243.8  684.03   355.5  643.45     386  634.38
   477.4  594.44   497.8  592.39   650.1  592.53   688.4  590.38   700.9  590.17
   713.4  591.06   741.6  598.51   761.9   601.9   853.3  605.39   914.2  613.11
  1065.9   627.1  1096.2  627.22  1136.6  622.95  1177.1   621.6  1207.4  625.78
    1258  637.89  1328.7  649.26  1399.5  651.83    1440  651.28  1510.7  658.54
    1531  662.52  1551.2  669.36  1632.1  704.27  1692.7  719.24  1763.5  744.57
#Mann= 3 , 0 , 0
       0     .06       0   688.4    .045       0   713.4     .06       0
Bank Sta=688.4,713.4
XS Rating Curve= 0 ,0
Exp/Cntr=0.3,0.1

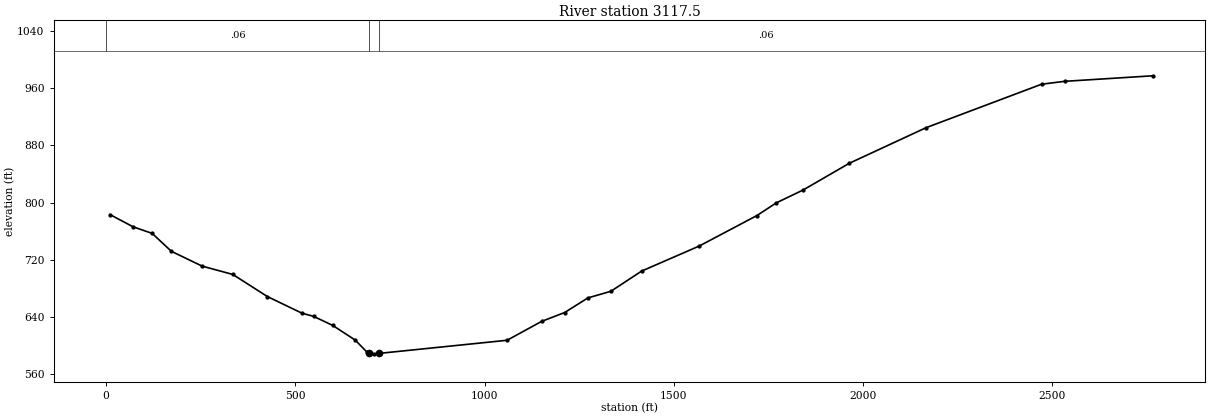
Type RM Length L Ch R = 1 ,3117.5  ,623.3,660.7,698.2
XS GIS Cut Line= 4
     1524399.344      399906.058     1524818.341      400290.275
     1525248.299      400283.227     1526954.036      400748.428
#Sta/Elev= 30
    10.2  783.44    71.1  766.37   121.8  757.09   172.6  732.05   253.8  711.36
     335  699.69   426.4  668.77   517.7  645.55   548.2  641.16   598.5  628.58
   658.5  607.92   688.5  591.61     696  589.66   708.5  588.75     721  589.36
  1059.5   607.7  1150.9  634.12  1211.9  646.53  1272.9  666.89  1333.8  676.16
  1415.1  704.41  1567.5  739.47  1719.9   782.1  1770.8  799.72  1841.9  817.79
  1963.8  855.09    2167  904.91  2471.9  965.61  2532.8  969.65  2766.5  977.41
#Mann= 3 , 0 , 0
       0     .06       0     696    .045       0     721     .06       0
Bank Sta=696,721
XS Rating Curve= 0 ,0
Exp/Cntr=0.3,0.1