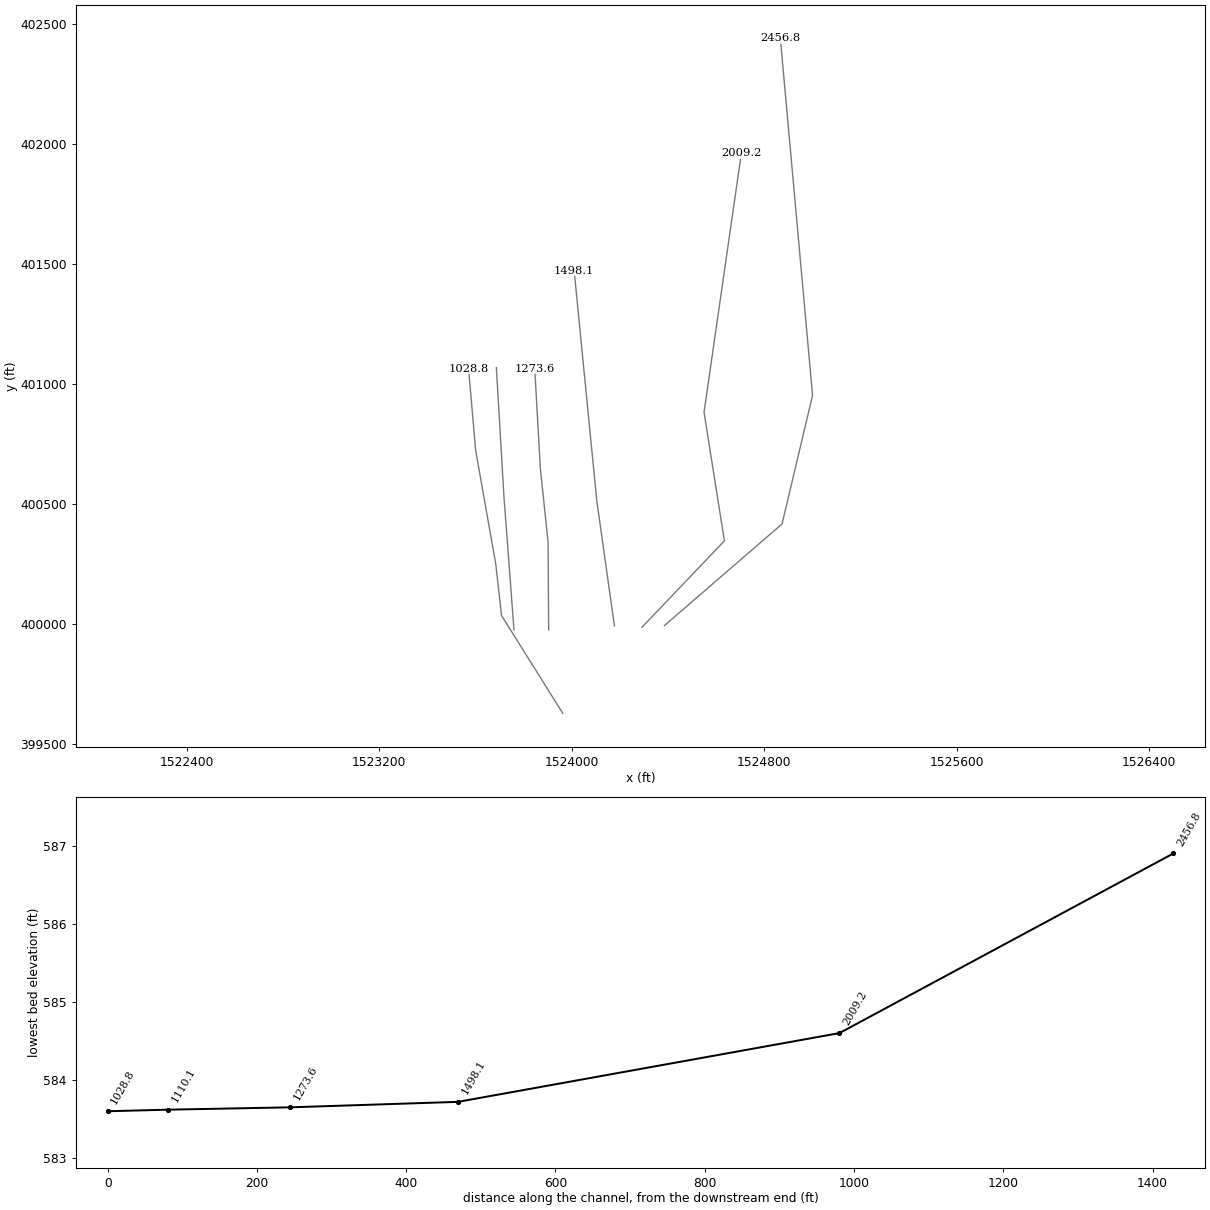
HEC-RAS study MILLCR.prj: MILLCR

--- MILLCR.g01 (geometry) --- (continued)

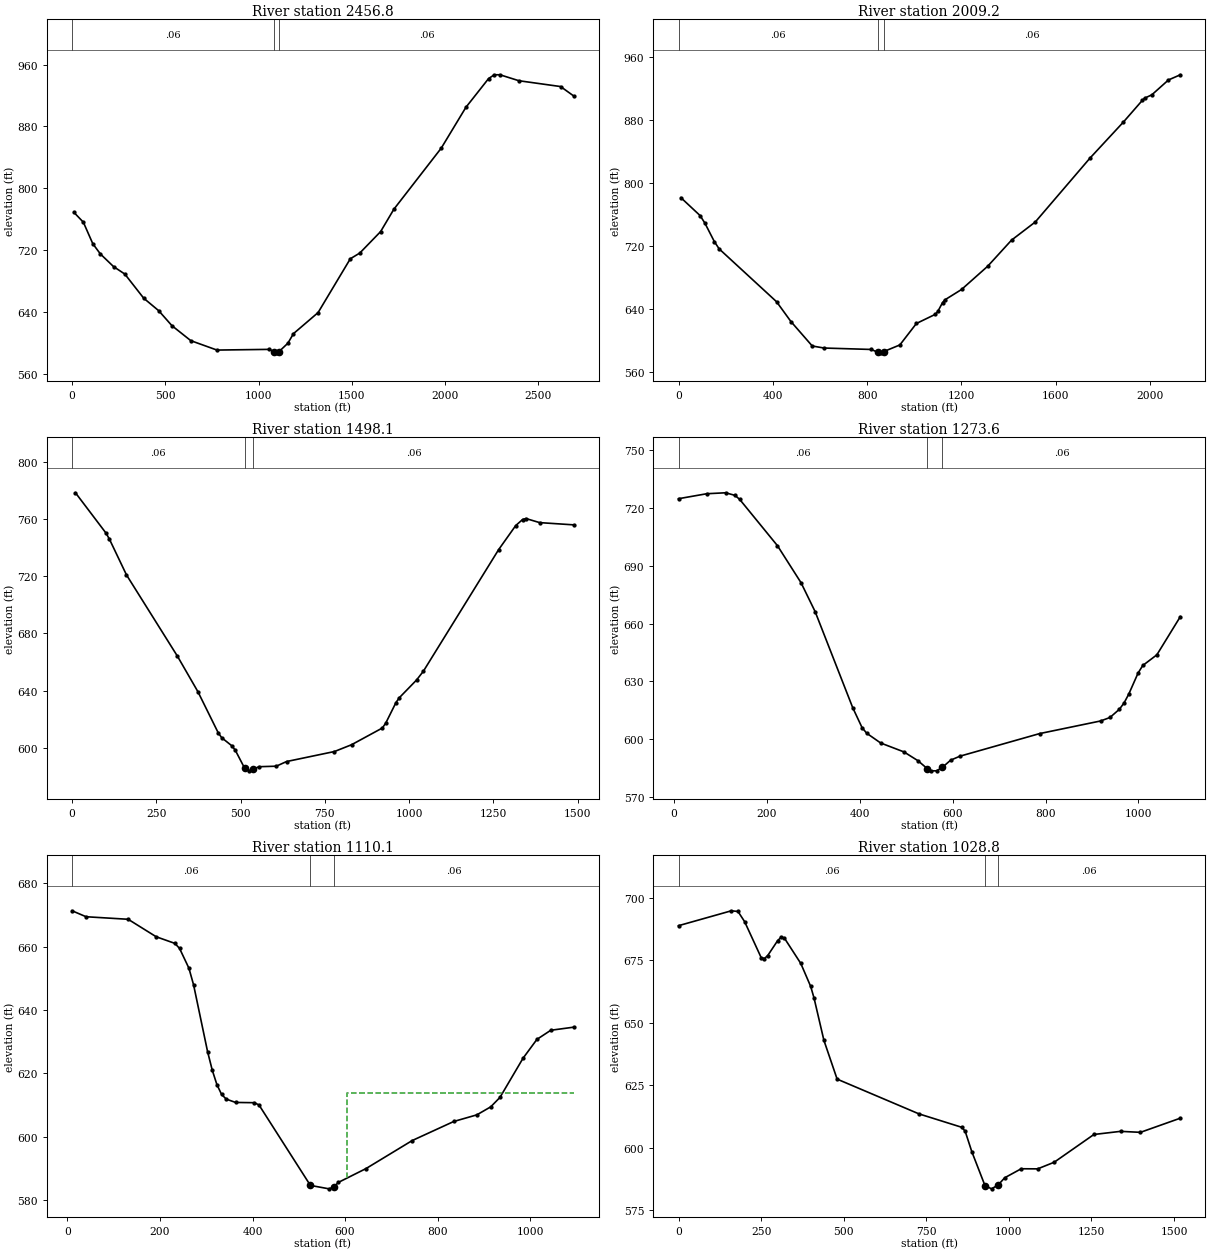
Type RM Length L Ch R = 1 ,2456.8  ,437,447.5,458
XS GIS Cut Line= 4
     1524385.852      399993.839     1524874.729      400417.148
     1525001.602      400952.834      1524867.68      402440.068
#Sta/Elev= 30
    10.1  768.67    60.6  755.95   111.1  728.16   151.6  714.95   222.3  698.55
   282.9  688.85     384  657.64   464.8  641.38   535.5  622.04   636.6  602.66
   776.8  590.49  1057.1  591.39  1084.6  588.39  1097.1   586.9  1109.6  588.52
  1157.1  599.36  1187.2  611.77  1319.1  639.02  1491.8  708.66  1542.6  716.06
  1654.3  743.84  1725.4  772.81  1979.4  851.88  2111.4  904.64  2233.3  941.96
  2263.8  946.82  2294.3  946.83  2395.8  939.12  2619.3  931.58  2690.4  919.25
#Mann= 3 , 0 , 0
       0     .06       0  1084.6    .045       0  1109.6     .06       0
Bank Sta=1084.6,1109.6
XS Rating Curve= 0 ,0
Exp/Cntr=0.3,0.1

Type RM Length L Ch R = 1 ,2009.2  ,511.2,511.1,510
XS GIS Cut Line= 4
     1524292.462      399986.625      1524635.08      400346.663
     1524550.498      400882.349     1524705.565       401960.77
#Sta/Elev= 30
    10.1  781.43    91.3  758.76   111.6  749.27   152.1  725.62   172.4  716.46
   415.9  649.43   476.7  624.34   567.3  593.28   617.5  590.69   818.4  588.88
   846.1   585.1   858.6   584.6   871.1  586.26   938.9  594.62  1009.2  621.85
  1089.8   633.5  1099.9  637.11    1120  648.27  1130.1  651.84  1200.7  664.98
  1311.7   694.5  1412.6  727.54  1513.5  750.61  1745.5  831.62  1886.7  877.16
  1967.4   904.8  1977.5   907.7  2007.8   911.9  2078.4  930.76  2128.8  937.34
#Mann= 3 , 0 , 0
       0     .06       0   846.1    .045       0   871.1     .06       0
Bank Sta=846.1,871.1
XS Rating Curve= 0 ,0
Exp/Cntr=0.3,0.1

Type RM Length L Ch R = 1 ,1498.1  ,225.5,224.5,224.6
XS GIS Cut Line= 3
     1524177.953      399992.809     1524104.769      400512.403
     1524010.551      401472.114
#Sta/Elev= 30
    10.1  778.59   100.9  750.26     111  746.01   161.5  721.02   312.8  664.01
   373.4  639.19   433.9  610.27     444  606.94   474.3  601.23   484.4  598.13
   512.2  585.51   524.7  583.72   537.2  584.95   555.2  586.62   605.9  586.97
   636.4  590.23   778.5  597.25   829.2     602   920.6  613.72   930.8  617.17
   961.2   631.6   971.4  635.04  1022.1  647.34  1042.4  653.51  1265.7  738.72
  1316.5  755.62  1336.8  759.84  1346.9  760.53  1387.5  757.68    1489   756.1
#Mann= 3 , 0 , 0
       0     .06       0   512.2    .045       0   537.2     .06       0
Bank Sta=512.2,537.2
XS Rating Curve= 0 ,0
Exp/Cntr=0.3,0.1

Type RM Length L Ch R = 1 ,1273.6  ,164.3,163.5,162.4
XS GIS Cut Line= 4
     1523904.508      399975.723     1523902.198      400340.648
     1523869.863      400650.141     1523846.767      401063.569
#Sta/Elev= 30
    10.1  724.72      71   727.3   111.5  727.79   131.8  726.43   141.9  724.31
     223  700.37   273.7   681.2   304.1   666.2     385  616.41   405.1  606.08
   415.1  603.14   445.2  598.08   495.4  593.45   525.5  588.89   545.6  584.77
   553.2  583.66   565.7  583.65   578.2   585.5   595.8  589.18   615.9  591.25
   787.2  602.95   918.5   609.5   938.7   611.3   958.9  615.54     969  618.81
   979.1  623.36   999.3  634.36  1009.4  638.26  1039.7  643.79  1090.2  663.58
#Mann= 3 , 0 , 0
    10.1     .06       0   545.6    .045       0   578.2     .06       0
Bank Sta=545.6,578.2
XS Rating Curve= 0 ,0
Exp/Cntr=0.3,0.1

Type RM Length L Ch R = 1 ,1110.1  ,81.4,81.3,81.4
XS GIS Cut Line= 3
     1523760.398       399976.08     1523718.775      400529.924
      1523687.19      401068.007
#Sta/Elev= 30
    10.1  671.26    40.4  669.38   131.3  668.58   191.9  663.07   232.3  660.98
   242.4  659.39   262.6  653.16   272.7   647.9   302.9  626.87     313  621.04
   323.1  616.46   333.2  613.37   343.3   611.9   363.5  610.85   403.9  610.77
     414  610.06   525.1   584.7   565.4  583.62   575.4  584.16   585.4  585.64
   645.2     590   745.1  598.84   834.9  604.85   884.8  606.94   914.7  609.46
   934.7  612.43   984.6  624.79  1014.6  630.73  1044.5   633.6  1094.4  634.58
#Mann= 3 , 0 , 0
    10.1     .06       0   525.1    .045       0   575.4     .06       0
#XS Ineff= 2 , 0
                          603.94          613.67
Permanent Ineff=
       F       F
Bank Sta=525.1,575.4
XS Rating Curve= 0 ,0
Exp/Cntr=0.3,0.1

Type RM Length L Ch R = 1 ,1028.8  ,1125.7,1028.8,931.9
XS GIS Cut Line= 5
     1523963.481      399628.014     1523708.914      400035.076
     1523684.423      400251.734     1523601.202      400723.333
     1523571.417      401064.126
#Sta/Elev= 30
       0  688.85     160  694.81     180  694.53     200  690.48   250.1   676.1
   260.1  675.72   270.1  676.92   300.1  682.88   310.1  684.17   320.1  683.96
   370.1  673.75   400.1  664.54   410.1  659.97   440.1  642.99   480.1  627.48
   728.1  613.57   857.8   608.2   867.8  606.62   887.7  598.52   927.6  584.93
   947.6   583.6   967.5  585.15   987.5  588.03  1037.4  591.63  1087.2  591.59
  1137.1  594.23  1257.5  605.34    1338  606.59  1398.4   606.2  1519.1  611.86
#Mann= 3 , 0 , 0
       0     .06       0   927.6    .045       0   967.5     .06       0
Bank Sta=927.6,967.5
XS Rating Curve= 0 ,0
Exp/Cntr=0.3,0.1

Chan Stop Cuts=-1
Use User Specified Reach Order=0